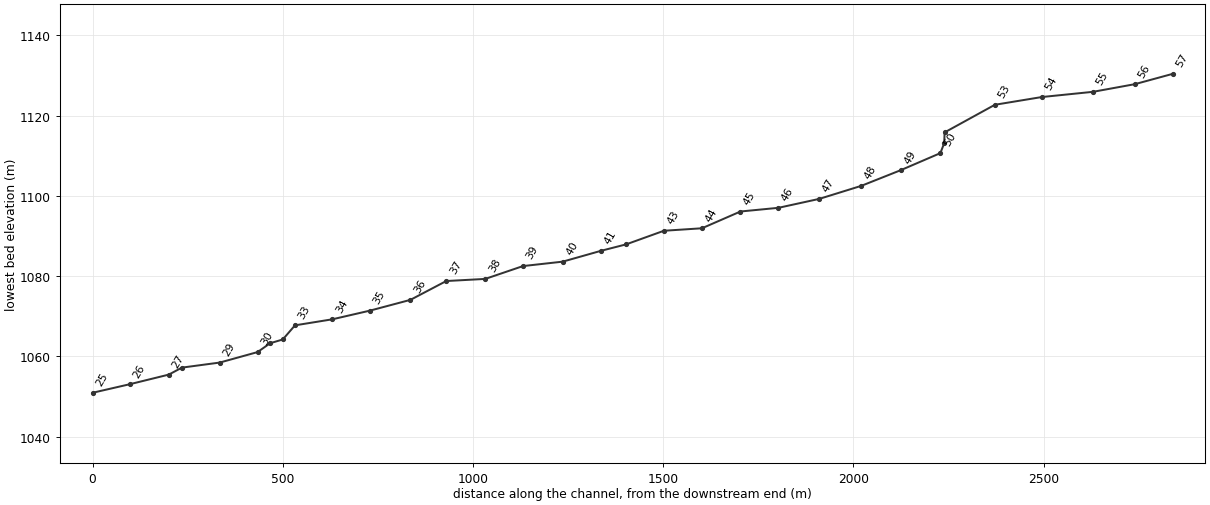
--- Hec-aguacatal.prj (project) ---

Proj Title=Hec-aguacatal
Current Plan=p01
Default Exp/Contr=0.3,0.1
SI Units
Geom File=g01
Flow File=f01
Plan File=p01
Y Axis Title=Elevation
X Axis Title(PF)=Main Channel Distance
X Axis Title(XS)=Station
BEGIN DESCRIPTION:
END DESCRIPTION:
DSS Export Rating Curves= 0
DSS Export Rating Curve Sorted= 0
DSS Export Volume Flow Curves= 0
DXF OffsetX= 0
DXF OffsetY= 0
DXF ScaleX= 1
DXF ScaleY= 10

--- Hec-aguacatal.p01 (plan) ---

Plan Title=Plan 01
Program Version=4.00
Short Identifier=Plan 01
Geom File=g01
Flow File=f01
Mixed Flow
K Sum by GR= 0
Std Step Tol= 0.003
Critical Tol= 0.003
Num of Std Step Trials= 20
Max Error Tol= 0.1
Flow Tol Ratio= 0.001
Split Flow NTrial= 30
Split Flow Tol= 0.006
Split Flow Ratio= 0.02
Log Output Level= 0
Friction Slope Method= 1
Unsteady Friction Slope Method= 2
Unsteady Bridges Friction Slope Method= 1
Parabolic Critical Depth
Global Vel Dist= 6 , 6 , 6
Global Log Level= 0
CheckData=True
Encroach Param=-1 ,0,0, 0
Computation Interval=1HOUR
Output Interval=1HOUR
Run HTab= 0
Run UNet= 0
Run PostProcess= 0
Run WQNet= 0
UNET Theta= 1
UNET Theta Warmup= 1
UNET ZTol= 0.006
UNET ZSATol= 0.015
UNET MxIter= 20
UNET MaxInSteps= 0
UNET DtIC= 0
UNET DtMin= 0
UNET MaxCRTS= 20
UNET WFStab= 2
UNET SFStab= 1
UNET WFX= 1
UNET SFX= 1
UNET DSS MLevel= 4
UNET DZMax Abort= 30
UNET Convert EG Bridges= 0
UNET Use Existing IB Tables=-1
UNET Froude Reduction=False
UNET Froude Limit= 1
UNET Froude Power= 10
UNET Time Slicing=0,0, 5
Instantaneous Interval=1HOUR
Write IC File= 0
Echo Input=False
Echo Output=False
Write Detailed= 0
Detailed Automatic Start=False, 10
WQ ULTIMATE=-1
WQ Max Comp Step=1HOUR
WQ Output Interval=15MIN
WQ Output Selected Increments= 0
WQ Output face flow=0
WQ Output face velocity=0
WQ Output face area=0
WQ Output face dispersion=0
WQ Output cell volume=0
WQ Output cell surface area=0
WQ Output cell continuity=0
WQ Output face conc=0
WQ Output face dconc_dx=0
WQ Output face courant=0
WQ Output face peclet=0
WQ Output face adv mass=0
WQ Output face disp mass=0
WQ Output cell mass=0
WQ Output cell source sink temp=0
WQ Output cell source sink nsm=0
WQ Output MaxMinRange=-1
WQ Daily Max Min Mean=-1
WQ Daily Range=0
WQ Daily Time=0
WQ Create Restart=0
WQ Fixed Restart=0
WQ System Summary=False
Sorting and Armoring Iterations= 10
XS Update Threshold= 0.02
Hydraulics Update Threshold= 0.02
Energy Slope Method= 1
Volume Change Method= 0
XS Weighting Method= 0
Number of US Weighted Cross Sections= 1
Number of DS Weighted Cross Sections= 1
Upstream XS Weight=0.25
Main XS Weight=0.5
Downstream XS Weight=0.25
Number of DS XS's Weighted with US Boundary= 1
Upstream Boundary Weight= 1
Weight of XSs Associated with US Boundary= 0
Number of US XS's Weighted with DS Boundary= 1
Downstream Boundary Weight= 0.5
Weight of XSs Associated with DS Boundary= 0.5
Sediment Output Level= 4
Mass or Volume Output= 0
Output Increment Type= 1
Profile and TS Output Increment= 10
XS Output Flag= 0
XS Output Increment= 10
Disregard all LS=0
Disregard all Conn=0
Disregard all Breaches=0
Disregard all Pumps=0

--- Hec-aguacatal.f01 (steady flow) ---

Flow Title=aguacatal
Program Version=4.00
Number of Profiles= 5
Profile Names=5 años,10 años,25 años,50 años,100 años
River Rch & RM=1,1               ,57
   31.09   41.67   55.03   64.95   74.79
Boundary for River Rch & Prof#=1,1               , 1
Up Type= 3
Up Slope=0.021398
Dn Type= 3
Dn Slope=0.013995
Boundary for River Rch & Prof#=1,1               , 2
Up Type= 3
Up Slope=0.021398
Dn Type= 3
Dn Slope=0.013995
Boundary for River Rch & Prof#=1,1               , 3
Up Type= 3
Up Slope=0.021398
Dn Type= 3
Dn Slope=0.013995
Boundary for River Rch & Prof#=1,1               , 4
Up Type= 3
Up Slope=0.021398
Dn Type= 3
Dn Slope=0.013995
Boundary for River Rch & Prof#=1,1               , 5
Up Type= 3
Up Slope=0.021398
Dn Type= 3
Dn Slope=0.013995
DSS Import GetInterval= 0
DSS Import GetPeak= 0
DSS Import FillOption= 0

--- Hec-aguacatal.g01 (geometry) ---

Geom Title=HEC-AGUACATAL
Program Version=4.00

River Reach=1               ,1
Reach XY= 4
1.267857142857140.293367346938780.920918367346940.47704081632653
0.31122448979592 0.4515306122449-0.29336734693870.83418367346939

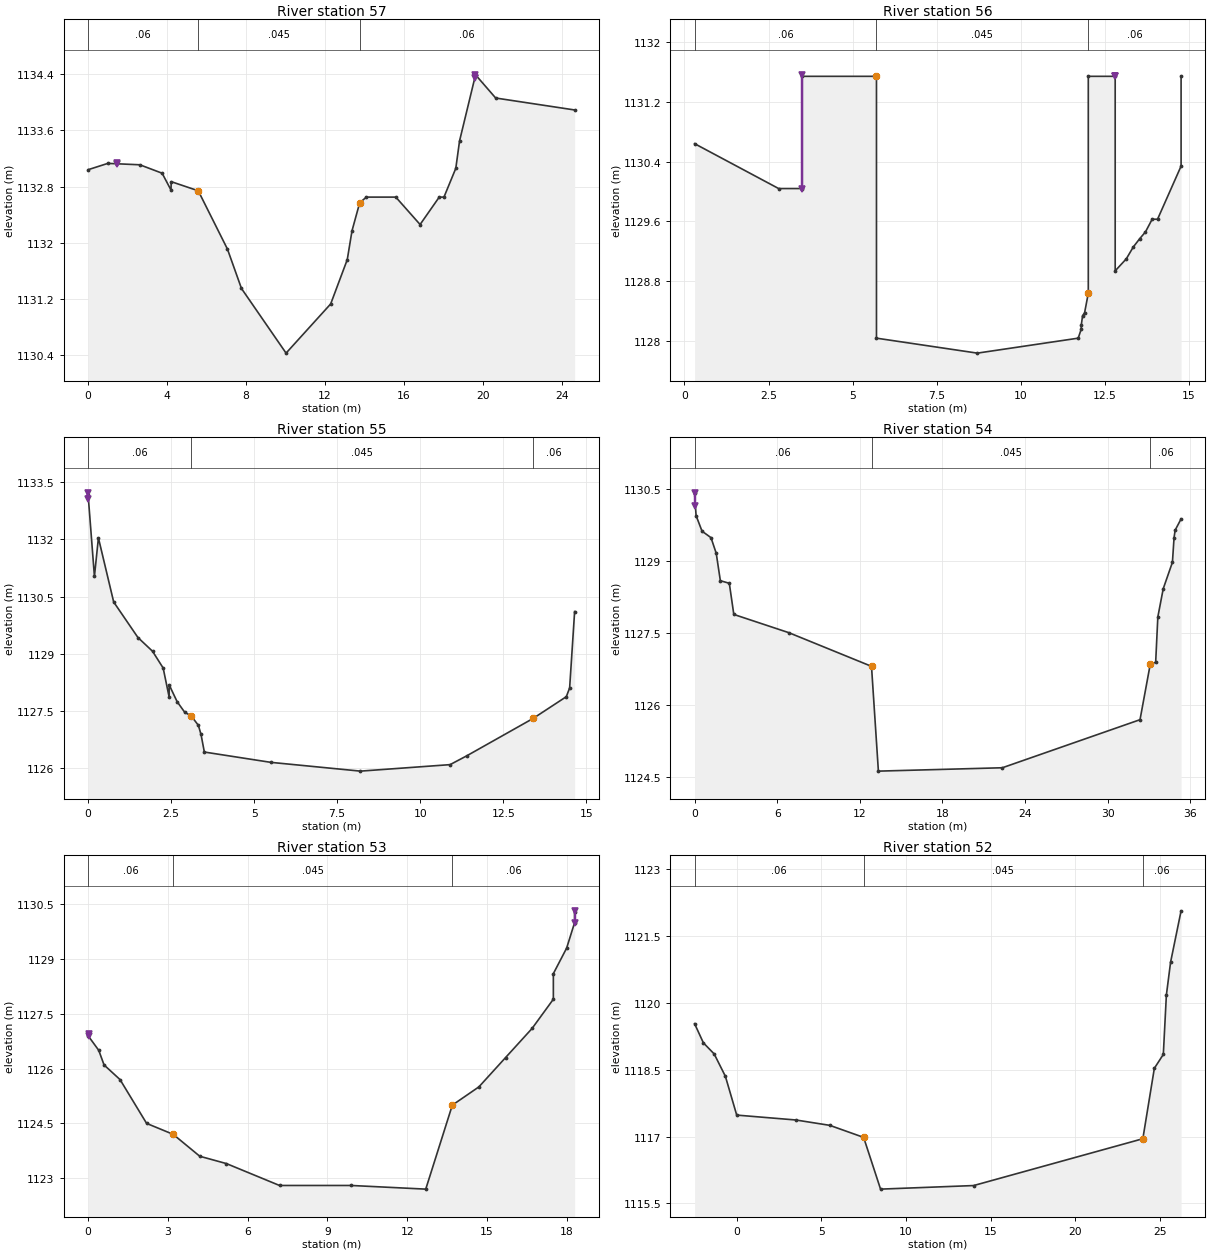
Type RM Length L Ch R = 1 ,57      ,102,100.2,98.14
BEGIN DESCRIPTION:
S0
END DESCRIPTION:
#Sta/Elev= 24
       0 1133.04       1 1133.13    2.62 1133.11    3.75 1132.99     4.2 1132.75
    4.21 1132.87    5.58 1132.74    7.06 1131.91    7.77 1131.35   10.03 1130.43
   12.29 1131.13   13.13 1131.76   13.37 1132.17   13.76 1132.57    14.1 1132.65
   15.59 1132.65   16.82 1132.26   17.79 1132.65   18.03 1132.65   18.63 1133.06
   18.82 1133.45   19.63 1134.39   20.65 1134.06   24.65 1133.89
#Mann= 3 , 0 , 0
       0     .06       0    5.58    .045       0   13.76     .06       0
Levee=-1,1.45,1133.14,-1,19.59,1134.39,,
Bank Sta=5.58,13.76
XS Rating Curve= 0 ,0
Exp/Cntr=0.3,0.1

Type RM Length L Ch R = 1 ,56      ,110.44,110.1,109.85
BEGIN DESCRIPTION:
S100
END DESCRIPTION:
#Sta/Elev= 24
      .3 1130.64     2.8 1130.04     3.5 1130.04     3.5 1131.54    5.71 1131.54
    5.71 1128.04    8.71 1127.84   11.71 1128.04    11.8 1128.16    11.8 1128.21
   11.84 1128.34    11.9 1128.38   12.01 1128.64   12.01 1131.54   12.81 1131.54
   12.81 1128.94   13.14  1129.1   13.35 1129.26   13.54 1129.37   13.71 1129.46
   13.91 1129.63   14.07 1129.63   14.77 1130.34   14.77 1131.54
#Mann= 3 , 0 , 0
      .3     .06       0    5.71    .045       0   12.01     .06       0
Levee=-1,3.5,1131.56,-1,12.81,1131.54,,
Bank Sta=5.71,12.01
XS Rating Curve= 0 ,0
Exp/Cntr=0.3,0.1

Type RM Length L Ch R = 1 ,55      ,130.15,134.5,139.14
BEGIN DESCRIPTION:
S200
END DESCRIPTION:
#Sta/Elev= 23
       0 1133.17     .19 1131.03     .31 1132.04     .77 1130.36     1.5 1129.43
    1.94 1129.07    2.26 1128.63    2.44 1127.87    2.44 1128.19    2.68 1127.75
    2.91 1127.47     3.1 1127.38    3.32 1127.13     3.4 1126.89     3.5 1126.43
     5.5 1126.16     8.2 1125.93    10.9  1126.1    11.4 1126.33    13.4 1127.31
    14.4 1127.88    14.5 1128.11   14.65 1130.11
#Mann= 3 , 0 , 0
       0     .06       0     3.1    .045       0    13.4     .06       0
Levee=-1,0.01,1133.22,-1,14.67,1130.13,,
Bank Sta=3.1,13.4
XS Rating Curve= 0 ,0
Exp/Cntr=0.3,0.1

Type RM Length L Ch R = 1 ,54      ,119.63,123.5,126.4
BEGIN DESCRIPTION:
S300
END DESCRIPTION:
#Sta/Elev= 21
       01130.408    .1081129.947    .5421129.622   1.1931129.487   1.5731129.161
   1.8711128.592   2.5221128.538   2.849 1127.89   6.849 1127.51  12.849 1126.81
  13.349 1124.63  22.349  1124.7  32.349  1125.7  33.0931126.855  33.4861126.895
  33.6431127.837  34.0351128.425  34.7031128.975  34.8211129.485  34.8991129.642
  35.3321129.878
#Mann= 3 , 0 , 0
       0     .06       0  12.849    .045       0  33.093     .06       0
Levee=-1,0.06,1130.42,-1,35.34,1129.89,,
Bank Sta=12.849,33.093
XS Rating Curve= 0 ,0
Exp/Cntr=0.3,0.1

Type RM Length L Ch R = 1 ,53      ,161.62,132.02,105.11
BEGIN DESCRIPTION:
S400
END DESCRIPTION:
#Sta/Elev= 20
       0  1126.9      .4  1126.5      .6  1126.1     1.2  1125.7     2.2  1124.5
     3.2  1124.2     4.2  1123.6     5.2  1123.4     7.2  1122.8     9.9  1122.8
    12.7  1122.7    13.7    1125    14.7  1125.5    15.7  1126.3    16.7  1127.1
    17.5  1127.9    17.5  1128.6      18  1129.3    18.3    1130    18.3  1130.3
#Mann= 3 , 0 , 0
       0     .06       0     3.2    .045       0    13.7     .06       0
Levee=-1,0.02,1126.94,-1,18.3,1130.32,,
Bank Sta=3.2,13.7
XS Rating Curve= 0 ,0
Exp/Cntr=0.3,0.1

Type RM Length L Ch R = 1 ,52      ,124.4,1.22,119.8
BEGIN DESCRIPTION:
S500
END DESCRIPTION:
#Sta/Elev= 16
   -2.49 1119.53   -1.97  1119.1   -1.33 1118.85    -.67 1118.35       0 1117.48
     3.5 1117.37     5.5 1117.25     7.5 1116.98     8.5 1115.82      14  1115.9
      24 1116.95   24.68 1118.53   25.21 1118.84   25.39 1120.17   25.64 1120.91
   26.26 1122.06
#Mann= 3 , 0 , 0
   -2.49     .06       0     7.5    .045       0      24     .06       0
Levee=-1,-2.51,1119.53,-1,26.3,1122.06,,
Bank Sta=7.5,24
XS Rating Curve= 0 ,0
Exp/Cntr=0.3,0.1

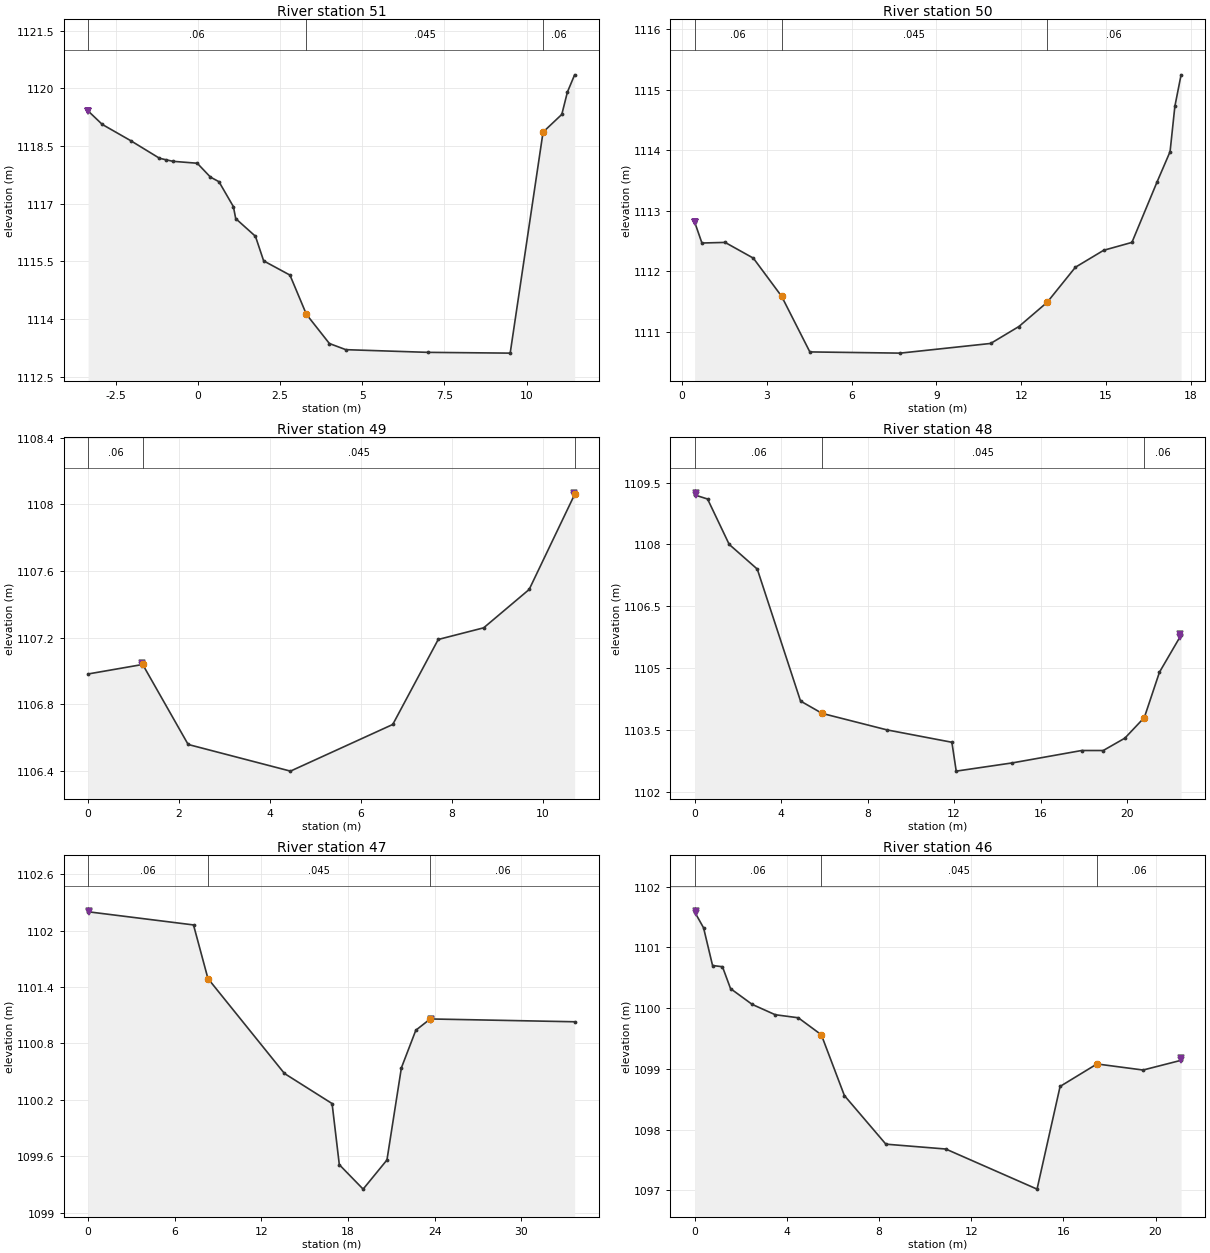
Type RM Length L Ch R = 1 ,51      ,101.6,10,101.88
BEGIN DESCRIPTION:
S600
END DESCRIPTION:
#Sta/Elev= 23
   -3.34 1119.41   -2.91 1119.06   -2.05 1118.64   -1.17 1118.18    -.97 1118.14
    -.76  1118.1    -.02 1118.05     .38 1117.69     .64 1117.57    1.08 1116.92
    1.15 1116.61    1.75 1116.15       2 1115.51     2.8 1115.14     3.3 1114.12
       4 1113.36     4.5  1113.2       7 1113.13     9.5 1113.11    10.5 1118.86
   11.07 1119.32   11.24  1119.9   11.46 1120.35
#Mann= 3 , 0 , 0
   -3.34     .06       0     3.3    .045       0    10.5     .06       0
Levee=-1,-3.33,1119.41,-1,11.47,1120.35,,
Bank Sta=3.3,10.5
XS Rating Curve= 0 ,0
Exp/Cntr=0.3,0.1

Type RM Length L Ch R = 1 ,50      ,106.21,104.2,103.9
BEGIN DESCRIPTION:
S700
END DESCRIPTION:
#Sta/Elev= 17
     .44 1112.82      .7 1112.47    1.52 1112.48    2.52 1112.22    3.52 1111.59
    4.52 1110.67    7.72 1110.65   10.92 1110.81   11.92 1111.09   12.92 1111.49
   13.92 1112.07   14.92 1112.35   15.92 1112.48   16.81 1113.48   17.27 1113.98
   17.44 1114.73   17.66 1115.25
#Mann= 3 , 0 , 0
     .44     .06       0    3.52    .045       0   12.92     .06       0
Levee=-1,0.44,1112.82,-1,17.67,1115.26,,
Bank Sta=3.52,12.92
XS Rating Curve= 0 ,0
Exp/Cntr=0.3,0.1

Type RM Length L Ch R = 1 ,49      ,103.2,103.5,103.9
BEGIN DESCRIPTION:
S800
END DESCRIPTION:
#Sta/Elev= 9
       01106.983     1.2 1107.04     2.2 1106.56    4.45  1106.4     6.7 1106.68
     7.7 1107.19     8.7 1107.26     9.7 1107.49    10.7 1108.06
#Mann= 3 , 0 , 0
       0     .06       0     1.2    .045       0    10.7     .06       0
Levee=-1,1.19,1107.05,-1,10.69,1108.07,,
Bank Sta=1.2,10.7
XS Rating Curve= 0 ,0
Exp/Cntr=0.3,0.1

Type RM Length L Ch R = 1 ,48      ,100.06,110.5,127.06
BEGIN DESCRIPTION:
S900
END DESCRIPTION:
#Sta/Elev= 16
       0  1109.2      .6  1109.1     1.6    1108     2.9  1107.4     4.9  1104.2
     5.9  1103.9     8.9  1103.5    11.9  1103.2    12.1  1102.5    14.7  1102.7
    17.9    1103    18.9    1103    19.9  1103.3    20.8  1103.8    21.5  1104.9
    22.5  1105.8
#Mann= 3 , 0 , 0
       0     .06       0     5.9    .045       0    20.8     .06       0
Levee=-1,0.08,1109.25,-1,22.45,1105.82,,
Bank Sta=5.9,20.8
XS Rating Curve= 0 ,0
Exp/Cntr=0.3,0.1

Type RM Length L Ch R = 1 ,47      ,107.23,107.5,107.77
BEGIN DESCRIPTION:
S1000
END DESCRIPTION:
#Sta/Elev= 12
       0  1102.2     7.3 1102.06     8.3 1101.49    13.6 1100.48    16.9 1100.16
    17.4 1099.51   19.05 1099.25    20.7 1099.56    21.7 1100.54    22.7 1100.94
    23.7 1101.06    33.7 1101.03
#Mann= 3 , 0 , 0
       0     .06       0     8.3    .045       0    23.7     .06       0
Levee=-1,0.03,1102.21,-1,23.76,1101.05,,
Bank Sta=8.3,23.7
XS Rating Curve= 0 ,0
Exp/Cntr=0.3,0.1

Type RM Length L Ch R = 1 ,46      ,112.97,99.8,96.6
BEGIN DESCRIPTION:
S1100
END DESCRIPTION:
#Sta/Elev= 17
       01101.584     .39 1101.32     .78  1100.7    1.21 1100.68    1.56 1100.32
     2.5 1100.06     3.5 1099.89     4.5 1099.84     5.5 1099.56     6.5 1098.56
     8.3 1097.76    10.9 1097.68   14.86 1097.02   15.86 1098.71   17.46 1099.08
   19.46 1098.98   21.11 1099.14
#Mann= 3 , 0 , 0
       0     .06       0     5.5    .045       0   17.46     .06       0
Levee=-1,0.04,1101.6,-1,21.1,1099.17,,
Bank Sta=5.5,17.46
XS Rating Curve= 0 ,0
Exp/Cntr=0.3,0.1

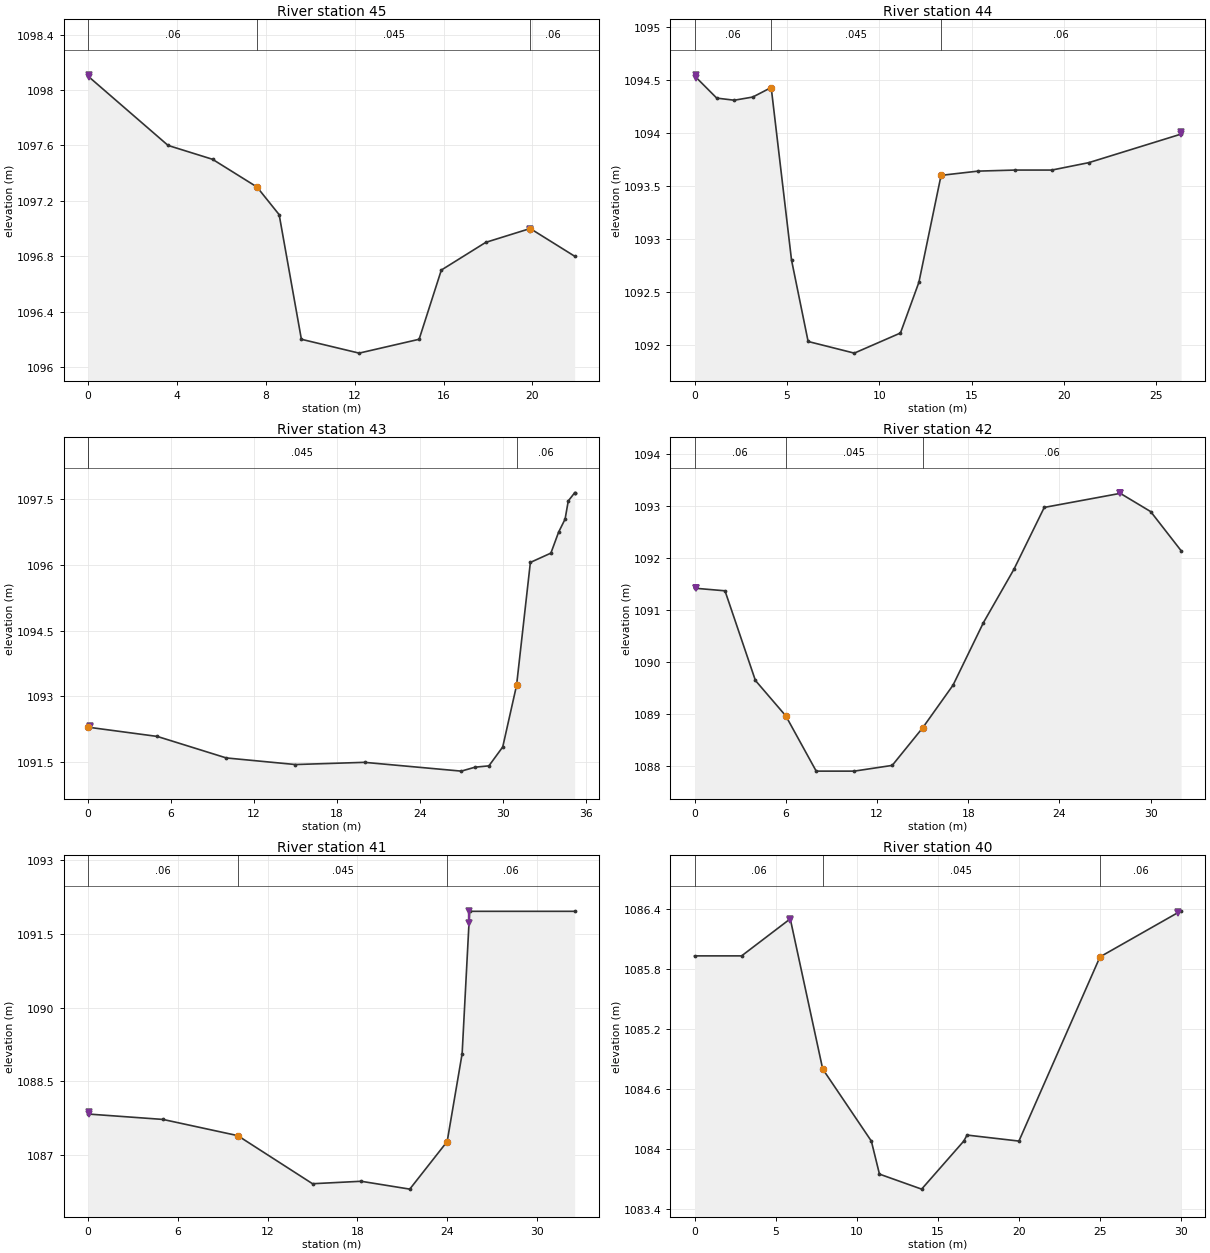
Type RM Length L Ch R = 1 ,45      ,97.27,101.3,104.3
BEGIN DESCRIPTION:
S1200
END DESCRIPTION:
#Sta/Elev= 12
       0  1098.1     3.6  1097.6     5.6  1097.5     7.6  1097.3     8.6  1097.1
     9.6  1096.2    12.2  1096.1    14.9  1096.2    15.9  1096.7    17.9  1096.9
    19.9    1097    21.9  1096.8
#Mann= 3 , 0 , 0
       0     .06       0     7.6    .045       0    19.9     .06       0
Levee=-1,0.02,1098.11,-1,19.9,1096.99,,
Bank Sta=7.6,19.9
XS Rating Curve= 0 ,0
Exp/Cntr=0.3,0.1

Type RM Length L Ch R = 1 ,44      ,95.01,100,103.64
BEGIN DESCRIPTION:
S1300
END DESCRIPTION:
#Sta/Elev= 16
       0 1094.54     1.2 1094.33    2.15 1094.31    3.15 1094.34    4.15 1094.43
    5.25  1092.8    6.15 1092.03    8.65 1091.92   11.15 1092.11   12.15 1092.59
   13.35  1093.6   15.35 1093.64   17.35 1093.65   19.35 1093.65   21.35 1093.72
   26.35 1093.99
#Mann= 3 , 0 , 0
       0     .06       0    4.15    .045       0   13.35     .06       0
Levee=-1,0.09,1094.55,-1,26.34,1094.01,,
Bank Sta=4.15,13.35
XS Rating Curve= 0 ,0
Exp/Cntr=0.3,0.1

Type RM Length L Ch R = 1 ,43      ,95.42,99.2,102.4
BEGIN DESCRIPTION:
S1400
END DESCRIPTION:
#Sta/Elev= 17
       0  1092.3       5 1092.09      10  1091.6      15 1091.45      20  1091.5
      27  1091.3      28 1091.39      29 1091.42      30 1091.85      31 1093.25
      32 1096.05  33.4851096.262   34.041096.737  34.5121097.036  34.742 1097.45
    35.21097.633  35.2021097.634
#Mann= 3 , 0 , 0
       0     .06       0       0    .045       0      31     .06       0
Levee=-1,0.12,1092.33,-1,35.24,1097.61,,
Bank Sta=0,31
XS Rating Curve= 0 ,0
Exp/Cntr=0.3,0.1

Type RM Length L Ch R = 1 ,42      ,74.26,66.3,56.26
BEGIN DESCRIPTION:
S1500
END DESCRIPTION:
#Sta/Elev= 15
       0 1091.42       2 1091.37       4 1089.65       6 1088.97       8 1087.91
    10.5 1087.91      13 1088.02      15 1088.74      17 1089.56      19 1090.76
      21 1091.78      23 1092.97      28 1093.24      30 1092.89      32 1092.14
#Mann= 3 , 0 , 0
       0     .06       0       6    .045       0      15     .06       0
Levee=-1,0.08,1091.43,-1,27.97,1093.25,,
Bank Sta=6,15
XS Rating Curve= 0 ,0
Exp/Cntr=0.3,0.1

Type RM Length L Ch R = 1 ,41      ,99.05,100.6,102.15
BEGIN DESCRIPTION:
S1600
END DESCRIPTION:
#Sta/Elev= 10
       0 1087.83       5 1087.72      10 1087.39      15 1086.41   18.25 1086.46
    21.5  1086.3      24 1087.27      25 1089.06    25.5 1091.96  32.519 1091.96
#Mann= 3 , 0 , 0
       0     .06       0      10    .045       0      24     .06       0
Levee=-1,0.08,1087.88,-1,25.46,1091.97,,
Bank Sta=10,24
XS Rating Curve= 0 ,0
Exp/Cntr=0.3,0.1

Type RM Length L Ch R = 1 ,40      ,107.8,104.3,98.86
BEGIN DESCRIPTION:
S1700
END DESCRIPTION:
#Sta/Elev= 12
       0 1085.93     2.9 1085.93     5.9  1086.3     7.9  1084.8    10.9 1084.08
    11.4 1083.75      14  1083.6    16.6 1084.08    16.8 1084.14      20 1084.08
      25 1085.92      30 1086.38
#Mann= 3 , 0 , 0
       0     .06       0     7.9    .045       0      25     .06       0
Levee=-1,5.91,1086.3,-1,29.81,1086.37,,
Bank Sta=7.9,25
XS Rating Curve= 0 ,0
Exp/Cntr=0.3,0.1

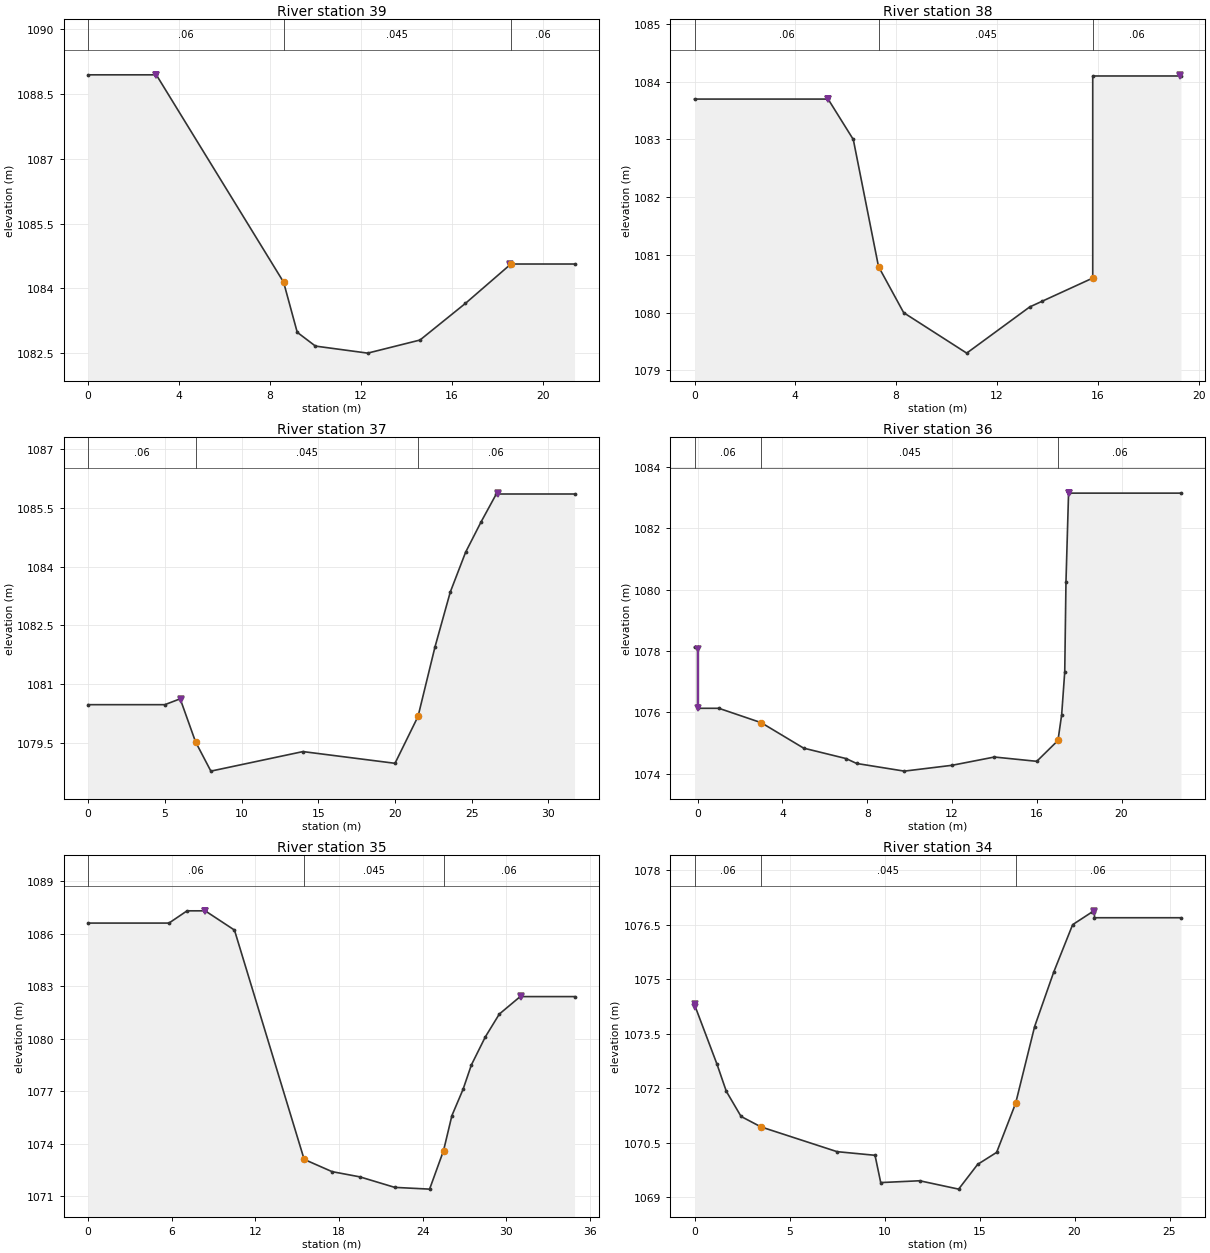
Type RM Length L Ch R = 1 ,39      ,102.2,99.2,97.87
BEGIN DESCRIPTION:
S1800
END DESCRIPTION:
#Sta/Elev= 10
       01088.943       31088.943     8.61084.143     9.21082.982      101082.663
    12.3  1082.5    14.61082.803    16.61083.652    18.61084.563    21.41084.563
#Mann= 3 , 0 , 0
       0     .06       0     8.6    .045       0    18.6     .06       0
Levee=-1,2.99,1088.94,-1,18.57,1084.57,,
Bank Sta=8.6,18.6
XS Rating Curve= 0 ,0
Exp/Cntr=0.3,0.1

Type RM Length L Ch R = 1 ,38      ,103.41,102.5,101.32
BEGIN DESCRIPTION:
S1900
END DESCRIPTION:
#Sta/Elev= 11
       0  1083.7     5.3  1083.7     6.3    1083     7.3  1080.8     8.3    1080
    10.8  1079.3    13.3  1080.1    13.8  1080.2    15.8  1080.6    15.8  1084.1
    19.3  1084.1
#Mann= 3 , 0 , 0
       0     .06       0     7.3    .045       0    15.8     .06       0
Levee=-1,5.28,1083.71,-1,19.27,1084.12,,
Bank Sta=7.3,15.8
XS Rating Curve= 0 ,0
Exp/Cntr=0.3,0.1

Type RM Length L Ch R = 1 ,37      ,89.15,94.2,98.31
BEGIN DESCRIPTION:
S2000
END DESCRIPTION:
#Sta/Elev= 14
       0 1080.47       5 1080.47       6 1080.62       7 1079.52       8 1078.77
      14 1079.27      20 1078.97    21.5 1080.17    22.6 1081.94    23.6 1083.35
    24.6 1084.37    25.6 1085.14    26.6 1085.86    31.7 1085.86
#Mann= 3 , 0 , 0
       0     .06       0       7    .045       0    21.5     .06       0
Levee=-1,6.03,1080.62,-1,26.68,1085.89,,
Bank Sta=7,21.5
XS Rating Curve= 0 ,0
Exp/Cntr=0.3,0.1

Type RM Length L Ch R = 1 ,36      ,109.53,106.2,104.85
BEGIN DESCRIPTION:
S2100
END DESCRIPTION:
#Sta/Elev= 18
    -.151078.121       0 1078.13       0 1076.13       1 1076.13       3 1075.66
       5 1074.83       7 1074.49     7.5 1074.33    9.75 1074.08      12 1074.27
      14 1074.54      16  1074.4      17 1075.08  17.1751075.924   17.321077.326
  17.3781080.261    17.5 1083.15  22.803 1083.15
#Mann= 3 , 0 , 0
    -.15     .06       0       3    .045       0      17     .06       0
Levee=-1,0.03,1078.05,-1,17.52,1083.16,,
Bank Sta=3,17
XS Rating Curve= 0 ,0
Exp/Cntr=0.3,0.1

Type RM Length L Ch R = 1 ,35      ,97.37,99.2,101.7
BEGIN DESCRIPTION:
S2200
END DESCRIPTION:
#Sta/Elev= 18
       0  1086.6     5.8  1086.6     7.1  1087.3     8.4  1087.3    10.5  1086.2
    15.5  1073.1    17.5  1072.4    19.5  1072.1      22  1071.5    24.5  1071.4
    25.5  1073.6    26.1  1075.6    26.9  1077.1    27.5  1078.5    28.5  1080.1
    29.5  1081.4      31  1082.4    34.9  1082.4
#Mann= 3 , 0 , 0
       0     .06       0    15.5    .045       0    25.5     .06       0
Levee=-1,8.41,1087.29,-1,31.05,1082.42,,
Bank Sta=15.5,25.5
XS Rating Curve= 0 ,0
Exp/Cntr=0.3,0.1

Type RM Length L Ch R = 1 ,34      ,98.92,98.05,97.7
BEGIN DESCRIPTION:
S2300
END DESCRIPTION:
#Sta/Elev= 20
       0  1074.3   1.1891072.656   1.6721071.921    2.451071.228     3.5 1070.94
     7.5 1070.26     9.5 1070.16     9.8 1069.41   11.85 1069.46    13.9 1069.23
    14.9 1069.91    15.9 1070.24    16.9 1071.59    17.9  1073.7    18.9 1075.19
    19.9  1076.5    20.9 1076.84   21.05 1076.84   21.05 1076.69    25.6 1076.69
#Mann= 3 , 0 , 0
       0     .06       0     3.5    .045       0    16.9     .06       0
Levee=-1,0.05,1074.33,-1,21.03,1076.88,,
Bank Sta=3.5,16.9
XS Rating Curve= 0 ,0
Exp/Cntr=0.3,0.1

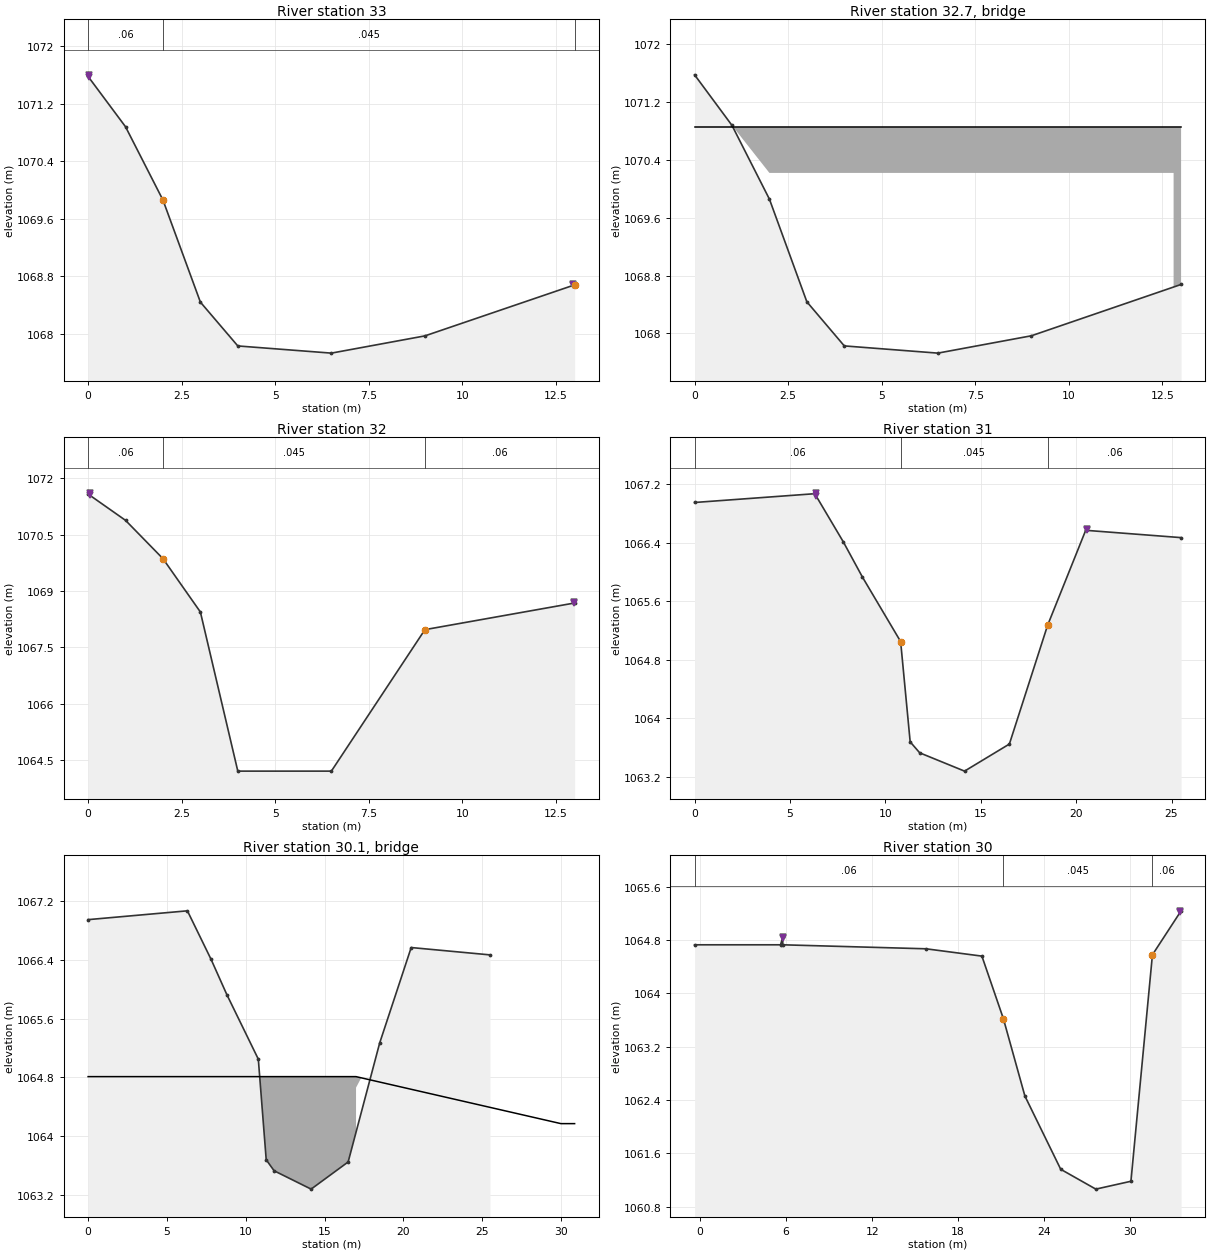
Type RM Length L Ch R = 1 ,33      ,32.067,32.167,32.233
BEGIN DESCRIPTION:
S2400
END DESCRIPTION:
#Sta/Elev= 8
       01071.577       11070.877       21069.857       31068.437       41067.827
     6.51067.727       91067.967      131068.677
#Mann= 3 , 0 , 0
       0     .06       0       2    .045       0      13     .06       0
Levee=-1,0.02,1071.6,-1,12.96,1068.69,,
Bank Sta=2,13
XS Rating Curve= 0 ,0
Exp/Cntr=0.3,0.1

Type RM Length L Ch R = 3 ,32.7    ,,,
BEGIN DESCRIPTION:
Puente Azul
END DESCRIPTION:
Bridge Culvert--1,0,-1,-1, 0
Deck Dist Width WeirC Skew NumUp NumDn MinLoCord MaxHiCord MaxSubmerge Is_Ogee
15,6,1.4,0, 6, 6, , , 0.98, 0, 0,0,,
       0      .2      .2    12.8    12.8      13
 1070.85 1070.85 1070.85 1070.85 1070.85 1070.85
    1065    1065 1070.22 1070.22    1065    1065
       0      .2      .2    12.8    12.8      13
 1070.85 1070.85 1070.85 1070.85 1070.85 1070.85
    1065    1065 1070.22 1070.22    1065    1065
BR Coef=-1 , 0 , 0 ,, 0 ,,,0.8,-1,,0,
WSPro=,,,, 1 ,,,, 0 ,,,, 0 ,,,,-1 ,-1 ,-1 , 0 , 0 , 0 , 0 , 0
BC Design=,, 0 ,, 0 ,,,,,,
BC Use User HTab Curves=0
BC User HTab FreeFlow(D)= 0

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
Type RM Length L Ch R = 1 ,32      ,33,33,33
BEGIN DESCRIPTION:
2500
END DESCRIPTION:
#Sta/Elev= 8
       01071.577       11070.877       21069.857       31068.437       4  1064.2
     6.5  1064.2       91067.967      131068.677
#Mann= 3 , 0 , 0
       0     .06       0       2    .045       0       9     .06       0
Levee=-1,0.04,1071.61,-1,12.99,1068.7,,
Bank Sta=2,9
XS Rating Curve= 0 ,0
Exp/Cntr=0.3,0.1

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
Type RM Length L Ch R = 1 ,31      ,33.263,33.267,33.28
BEGIN DESCRIPTION:
S2600
END DESCRIPTION:
#Sta/Elev= 12
       01066.948     6.31067.068     7.81066.408     8.81065.928    10.81065.048
    11.31063.678    11.81063.528   14.151063.278    16.51063.648    18.51065.268
    20.51066.568    25.51066.468
#Mann= 3 , 0 , 0
       0     .06       0    10.8    .045       0    18.5     .06       0
Levee=-1,6.37,1067.08,-1,20.55,1066.58,,
Bank Sta=10.8,18.5
XS Rating Curve= 0 ,0
Exp/Cntr=0.3,0.1

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
Type RM Length L Ch R = 3 ,30.1    ,,,
BEGIN DESCRIPTION:
PEatonal
END DESCRIPTION:
Bridge Culvert--1,0,-1,-1, 0
Deck Dist Width WeirC Skew NumUp NumDn MinLoCord MaxHiCord MaxSubmerge Is_Ogee
5,2,1.4,0, 6, 6, , , 0.98, 0, 0,0,,
       0      17      17      30      30   30.87
 1064.81 1064.81 1064.81 1064.17 1064.17 1064.17
    1060    1060 1064.66    1064    1064    1060
       0      20      20      33      33   33.49
 1064.81 1064.81 1064.81 1064.17 1064.17 1064.17
    1060    1060 1064.66    1064    1064    1060
BR Coef=-1 , 0 , 0 ,, 0 ,,,0.8,-1,,0,
WSPro=,,,, 1 ,,,, 0 ,,,, 0 ,,,,-1 ,-1 ,-1 , 0 , 0 , 0 , 0 , 0
BC Design=,, 0 ,, 0 ,,,,,,
BC Use User HTab Curves=0
BC User HTab FreeFlow(D)= 0

Type RM Length L Ch R = 1 ,30      ,99.18,99.4,99.68
BEGIN DESCRIPTION:
S2700
END DESCRIPTION:
#Sta/Elev= 13
   -.391 1064.73   5.609 1064.73   5.759 1064.84   5.759 1064.73  15.759 1064.67
  19.659 1064.56  21.159 1063.62  22.659 1062.46  25.159 1061.36  27.6091061.062
  30.059 1061.18  31.559 1064.58  33.559 1065.24
#Mann= 3 , 0 , 0
   -.391     .06       0  21.159    .045       0  31.559     .06       0
Levee=-1,5.75,1064.84,-1,33.49,1065.23,,
Bank Sta=21.159,31.559
XS Rating Curve= 0 ,0
Exp/Cntr=0.3,0.1

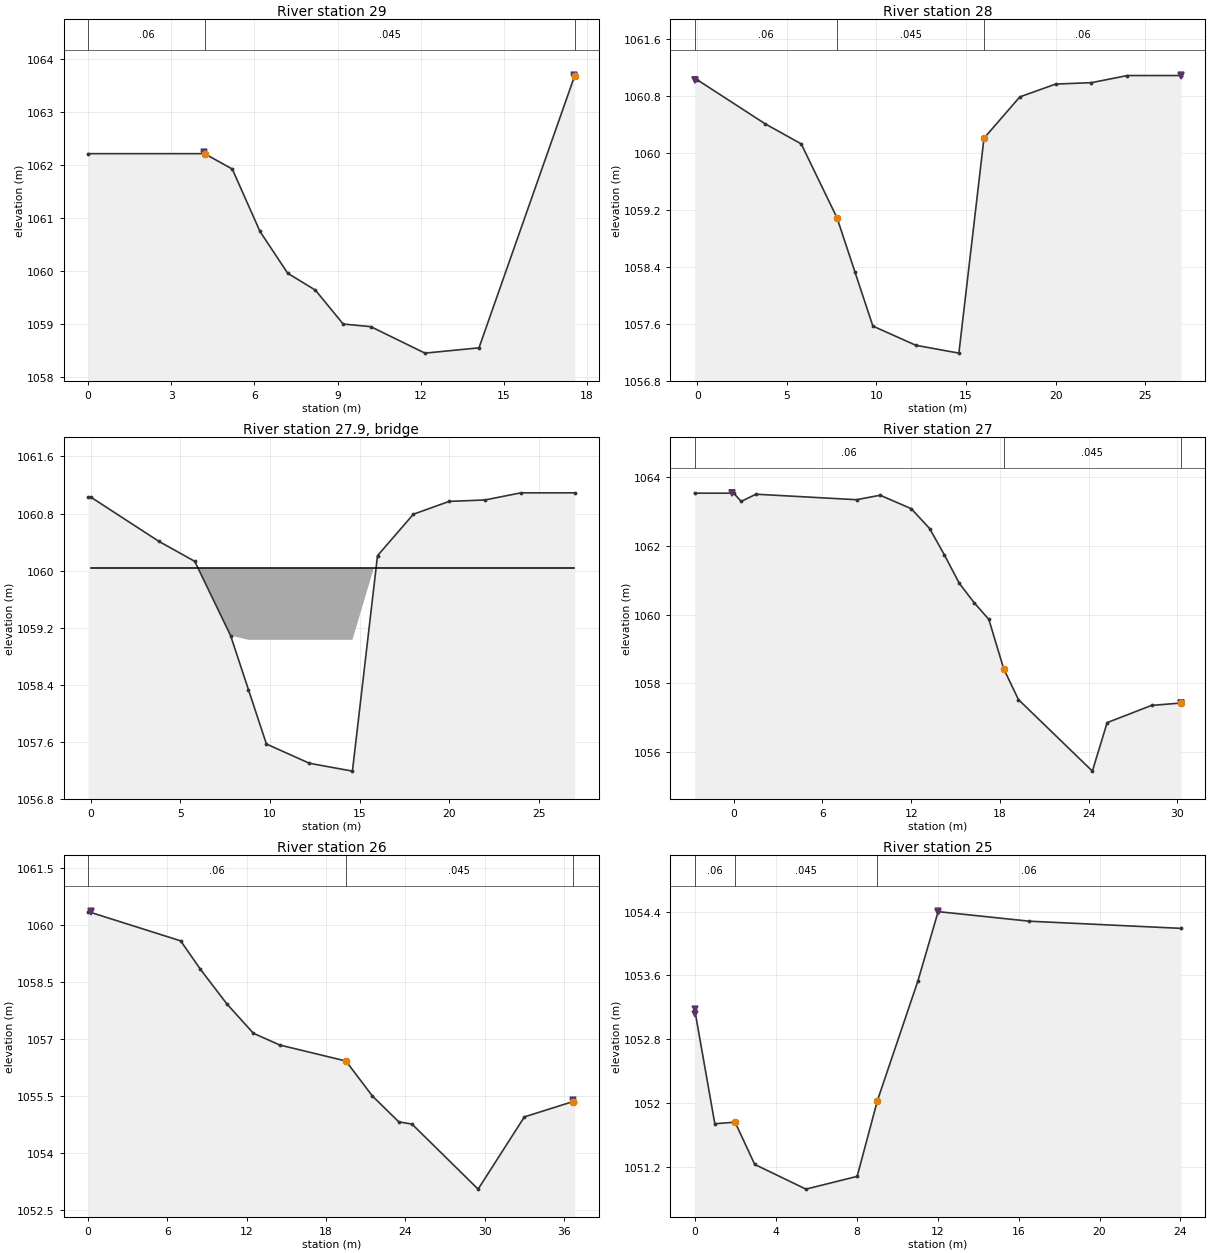
Type RM Length L Ch R = 1 ,29      ,96.62,99.5,103.15
BEGIN DESCRIPTION:
S2800
END DESCRIPTION:
#Sta/Elev= 11
       0 1062.22     4.2 1062.22     5.2 1061.93     6.2 1060.75     7.2 1059.96
     8.2 1059.64     9.2    1059    10.2 1058.95   12.15 1058.45    14.1 1058.55
   17.55 1063.69
#Mann= 3 , 0 , 0
       0     .06       0     4.2    .045       0   17.55     .06       0
Levee=-1,4.19,1062.25,-1,17.53,1063.71,,
Bank Sta=4.2,17.55
XS Rating Curve= 0 ,0
Exp/Cntr=0.3,0.1

Type RM Length L Ch R = 1 ,28      ,34.297,34.367,34.517
BEGIN DESCRIPTION:
S2900
END DESCRIPTION:
#Sta/Elev= 15
    -.15 1061.03       0 1061.03     3.8 1060.41     5.8 1060.13     7.8 1059.09
     8.8 1058.33     9.8 1057.57    12.2  1057.3    14.6 1057.19      161060.209
      18 1060.79      20 1060.97      22 1060.99      24 1061.09      27 1061.09
#Mann= 3 , 0 , 0
    -.15     .06       0     7.8    .045       0      16     .06       0
Levee=-1,-0.11,1061.03,-1,26.97,1061.1,,
Bank Sta=7.8,16
XS Rating Curve= 0 ,0
Exp/Cntr=0.3,0.1

Type RM Length L Ch R = 3 ,27.9    ,,,
BEGIN DESCRIPTION:
Ntra Señora
END DESCRIPTION:
Bridge Culvert--1,0,-1,-1, 0
Deck Dist Width WeirC Skew NumUp NumDn MinLoCord MaxHiCord MaxSubmerge Is_Ogee
5,6,1.4,0, 6, 6, , , 0.98, 0, 0,0,,
       0       6       6   16.15   16.15   26.97
 1060.03 1060.03 1060.03 1060.03 1060.03 1060.03
    1056    1056 1059.03 1059.03    1056    1056
       0      11      11   21.15   21.15   28.06
 1060.03 1060.03 1060.03 1060.03 1060.03 1060.03
    1056    1056 1059.03 1059.03    1056    1056
BR Coef=-1 , 0 , 0 ,, 0 ,,,0.8,-1,,0,
WSPro=,,,, 1 ,,,, 0 ,,,, 0 ,,,,-1 ,-1 ,-1 , 0 , 0 , 0 , 0 , 0
BC Design=,, 0 ,, 0 ,,,,,,
BC Use User HTab Curves=0
BC User HTab FreeFlow(D)= 0

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
Type RM Length L Ch R = 1 ,27      ,105,102.3,98.81
BEGIN DESCRIPTION:
S3000
END DESCRIPTION:
#Sta/Elev= 18
   -2.65 1063.53       0 1063.53      .5 1063.29     1.5  1063.5     8.3 1063.34
     9.9 1063.47      12 1063.08   13.25  1062.5   14.25 1061.73   15.25 1060.91
   16.25 1060.35   17.25 1059.86   18.25 1058.43   19.25 1057.53   24.25 1055.45
   25.25 1056.86   28.25 1057.36   30.25 1057.43
#Mann= 3 , 0 , 0
   -2.65     .06       0   18.25    .045       0   30.25     .06       0
Levee=-1,-0.09,1063.54,-1,30.24,1057.43,,
Bank Sta=18.25,30.25
XS Rating Curve= 0 ,0
Exp/Cntr=0.3,0.1

Type RM Length L Ch R = 1 ,26      ,97.64,98.1,99.22
BEGIN DESCRIPTION:
S3100
END DESCRIPTION:
#Sta/Elev= 14
       0 1060.36       7 1059.59     8.5 1058.84    10.5 1057.93    12.5 1057.16
    14.5 1056.85    19.5 1056.43    21.5 1055.51    23.5 1054.83    24.5 1054.77
    29.5 1053.06      33 1054.96   36.65 1055.36    36.8 1055.36
#Mann= 3 , 0 , 0
       0     .06       0    19.5    .045       0   36.65     .06       0
Levee=-1,0.19,1060.38,-1,36.69,1055.41,,
Bank Sta=19.5,36.65
XS Rating Curve= 0 ,0
Exp/Cntr=0.3,0.1

Type RM Length L Ch R = 1 ,25      ,98.71,99.1,100.64
BEGIN DESCRIPTION:
S3200
END DESCRIPTION:
#Sta/Elev= 11
       0 1053.18       1 1051.74       2 1051.76    2.97 1051.23     5.5 1050.92
    8.03 1051.08    9.03 1052.03   11.03 1053.53   12.03  1054.4   16.53 1054.28
   24.03 1054.19
#Mann= 3 , 0 , 0
       0     .06       0       2    .045       0    9.03     .06       0
Levee=-1,0.04,1053.18,-1,12.03,1054.41,,
Bank Sta=2,9.03
XS Rating Curve= 0 ,0
Exp/Cntr=0.3,0.1