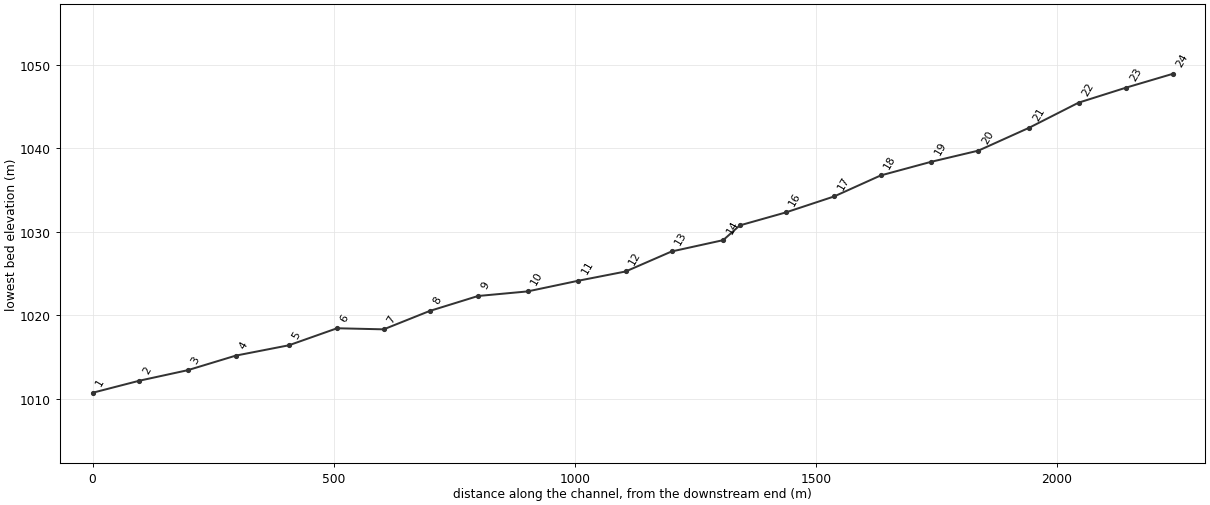
HEC-RAS study Hec-aguacatal.prj: Hec-aguacatal

--- Hec-aguacatal.g01 (geometry) --- (continued)

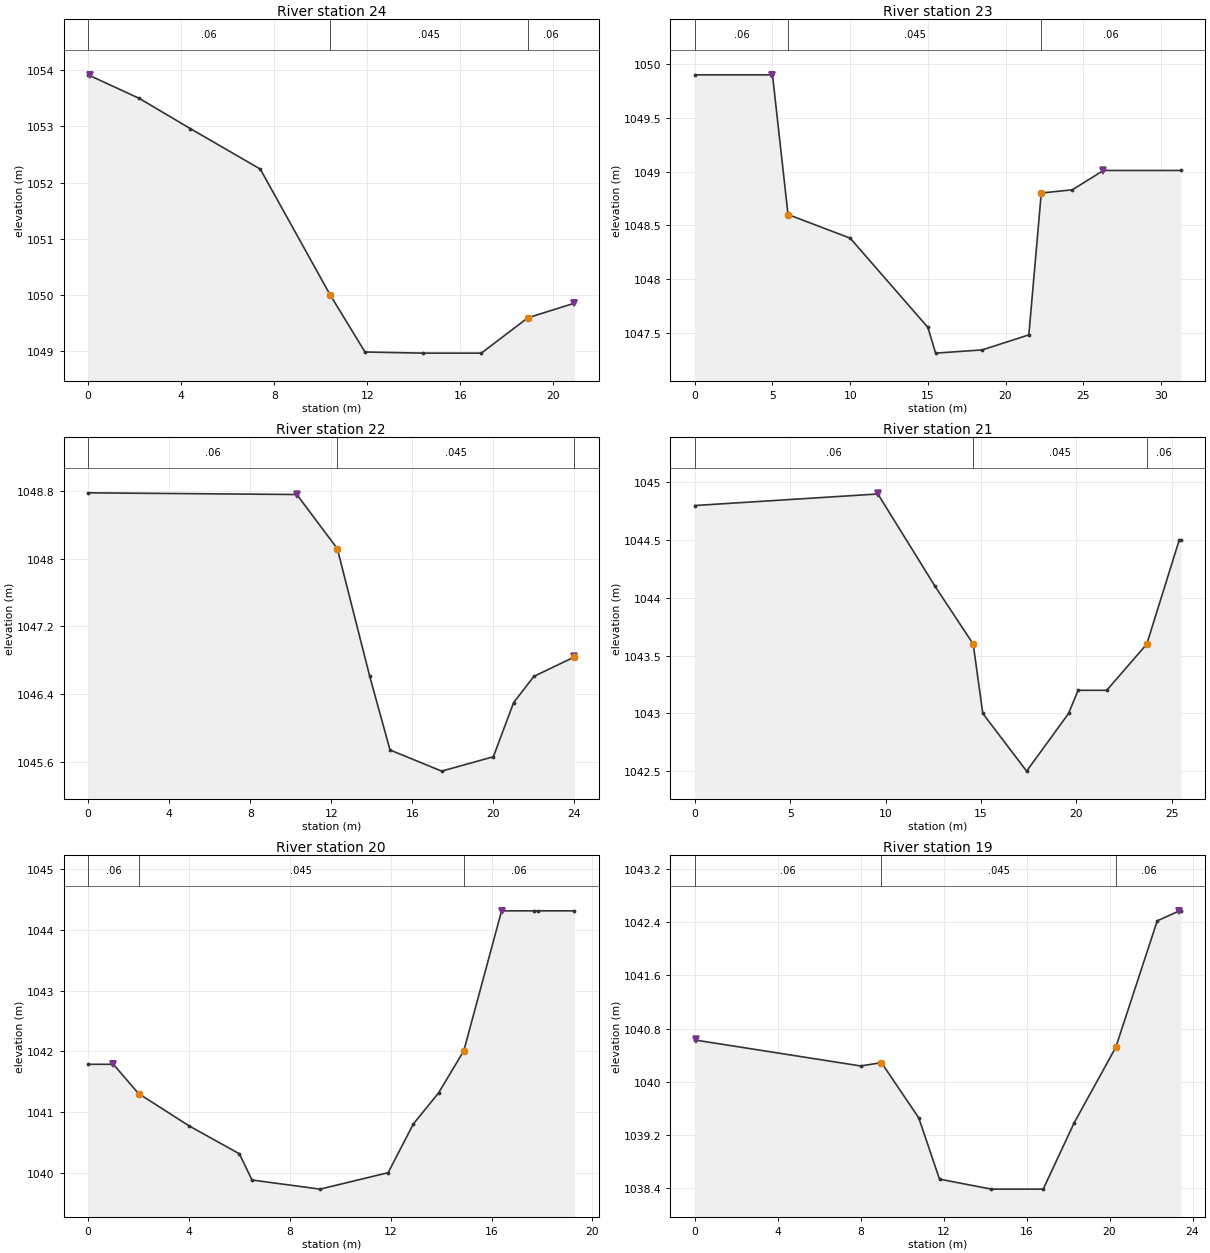
Type RM Length L Ch R = 1 ,24      ,99.28,96.5,93.3
BEGIN DESCRIPTION:
S3300
END DESCRIPTION:
#Sta/Elev= 10
       0 1053.92     2.2  1053.5     4.4 1052.96     7.4 1052.24    10.4    1050
    11.9 1048.98    14.4 1048.96    16.9 1048.96    18.9 1049.59    20.9 1049.85
#Mann= 3 , 0 , 0
       0     .06       0    10.4    .045       0    18.9     .06       0
Levee=-1,0.06,1053.92,-1,20.89,1049.86,,
Bank Sta=10.4,18.9
XS Rating Curve= 0 ,0
Exp/Cntr=0.3,0.1

Type RM Length L Ch R = 1 ,23      ,97.05,99.5,101.94
BEGIN DESCRIPTION:
S3400
END DESCRIPTION:
#Sta/Elev= 12
       0  1049.9       5  1049.9       6  1048.6      10 1048.38      15 1047.55
    15.5 1047.31    18.5 1047.34    21.5 1047.48    22.3  1048.8    24.3 1048.83
    26.3 1049.01    31.3 1049.01
#Mann= 3 , 0 , 0
       0     .06       0       6    .045       0    22.3     .06       0
Levee=-1,4.97,1049.9,-1,26.27,1049.01,,
Bank Sta=6,22.3
XS Rating Curve= 0 ,0
Exp/Cntr=0.3,0.1

Type RM Length L Ch R = 1 ,22      ,100.6,101.8,103.15
BEGIN DESCRIPTION:
S3500
END DESCRIPTION:
#Sta/Elev= 10
       0 1048.78    10.3 1048.76    12.3 1048.12    13.9 1046.61    14.9 1045.74
   17.45 1045.49      20 1045.66      21  1046.3      22 1046.61      24 1046.84
#Mann= 3 , 0 , 0
       0     .06       0    12.3    .045       0      24     .06       0
Levee=-1,10.31,1048.77,-1,24,1046.85,,
Bank Sta=12.3,24
XS Rating Curve= 0 ,0
Exp/Cntr=0.3,0.1

Type RM Length L Ch R = 1 ,21      ,107.6,105.8,103.47
BEGIN DESCRIPTION:
S3600
END DESCRIPTION:
#Sta/Elev= 12
       0  1044.8     9.6  1044.9    12.6  1044.1    14.6  1043.6    15.1    1043
    17.4  1042.5    19.6    1043    20.1  1043.2    21.6  1043.2    23.7  1043.6
    25.4  1044.5    25.5  1044.5
#Mann= 3 , 0 , 0
       0     .06       0    14.6    .045       0    23.7     .06       0
Levee=-1,9.59,1044.91,-1,25.53,1044.5,,
Bank Sta=14.6,23.7
XS Rating Curve= 0 ,0
Exp/Cntr=0.3,0.1

Type RM Length L Ch R = 1 ,20      ,99.25,98.6,97.6
BEGIN DESCRIPTION:
S3700
END DESCRIPTION:
#Sta/Elev= 15
       0 1041.79       1 1041.79       2 1041.31       4 1040.78       6 1040.32
     6.5 1039.89     9.2 1039.74    11.9 1040.01    12.9 1040.81    13.9 1041.32
    14.9 1042.01    16.4 1044.31    17.7 1044.31   17.85 1044.31  19.288 1044.31
#Mann= 3 , 0 , 0
       0     .06       0       2    .045       0    14.9     .06       0
Levee=-1,0.97,1041.79,-1,16.4,1044.31,,
Bank Sta=2,14.9
XS Rating Curve= 0 ,0
Exp/Cntr=0.3,0.1

Type RM Length L Ch R = 1 ,19      ,116.8,104.2,112.03
BEGIN DESCRIPTION:
S3800
END DESCRIPTION:
#Sta/Elev= 12
       0 1040.63       8 1040.24       9 1040.29    10.8 1039.46    11.8 1038.54
    14.3 1038.39    16.8 1038.39    18.3 1039.39    20.3 1040.52    22.3 1042.42
    23.3 1042.56   23.45 1042.56
#Mann= 3 , 0 , 0
       0     .06       0       9    .045       0    20.3     .06       0
Levee=-1,0.08,1040.65,-1,23.36,1042.57,,
Bank Sta=9,20.3
XS Rating Curve= 0 ,0
Exp/Cntr=0.3,0.1

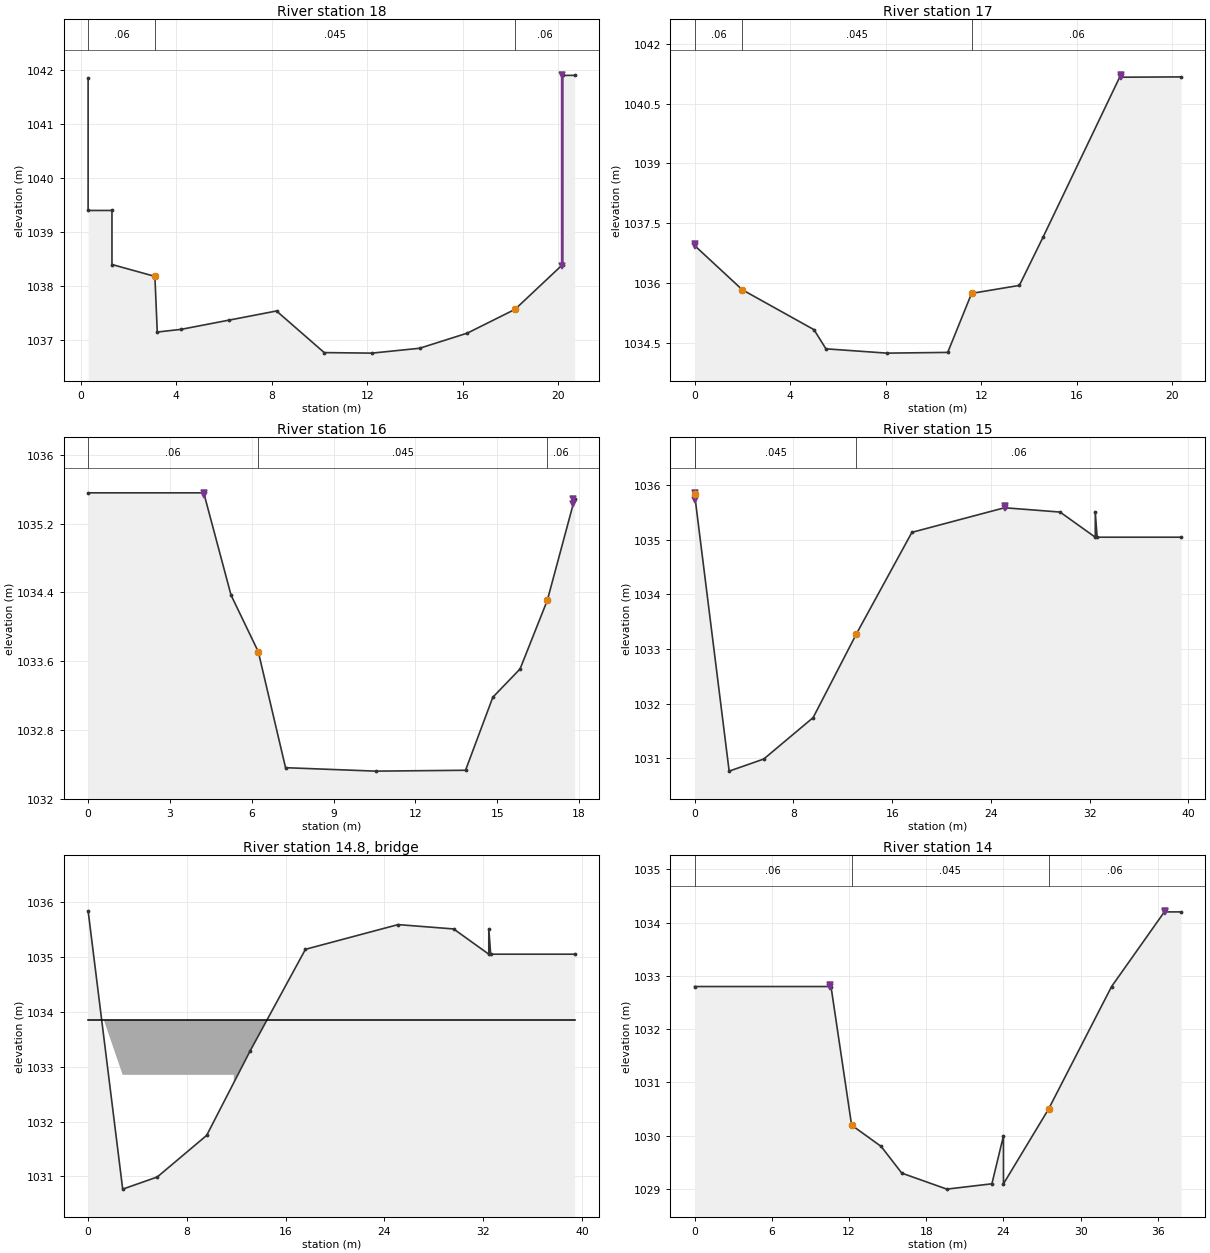
Type RM Length L Ch R = 1 ,18      ,96.58,96.5,96.44
BEGIN DESCRIPTION:
S3900
END DESCRIPTION:
#Sta/Elev= 17
      .3 1041.85      .3  1039.4     1.3  1039.4     1.3  1038.4     3.1 1038.18
     3.2 1037.15     4.2  1037.2     6.2 1037.37     8.2 1037.54    10.2 1036.77
    12.2 1036.76    14.2 1036.85    16.2 1037.13    18.2 1037.57    20.2  1038.4
    20.2  1041.9    20.7  1041.9
#Mann= 3 , 0 , 0
      .3     .06       0     3.1    .045       0    18.2     .06       0
Levee=-1,0.29,1041.88,-1,20.15,1041.91,,
Bank Sta=3.1,18.2
XS Rating Curve= 0 ,0
Exp/Cntr=0.3,0.1

Type RM Length L Ch R = 1 ,17      ,101.4,100.5,99.5
BEGIN DESCRIPTION:
S4000
END DESCRIPTION:
#Sta/Elev= 11
       0 1036.94       2 1035.83       5 1034.83     5.5 1034.35    8.051034.242
    10.6 1034.26    11.6 1035.74    13.6 1035.94    14.6 1037.16    17.8 1041.16
  20.3721041.168
#Mann= 3 , 0 , 0
       0     .06       0       2    .045       0    11.6     .06       0
Levee=-1,0.02,1036.99,-1,17.84,1041.22,,
Bank Sta=2,11.6
XS Rating Curve= 0 ,0
Exp/Cntr=0.3,0.1

Type RM Length L Ch R = 1 ,16      ,92.43,95.2,99.14
BEGIN DESCRIPTION:
S4100
END DESCRIPTION:
#Sta/Elev= 11
       0 1035.56    4.24 1035.56    5.24 1034.37    6.24 1033.71    7.24 1032.36
   10.54 1032.32   13.84 1032.33   14.84 1033.18   15.84 1033.51   16.84 1034.31
   17.84 1035.49
#Mann= 3 , 0 , 0
       0     .06       0    6.24    .045       0   16.84     .06       0
Levee=-1,4.26,1035.56,-1,17.79,1035.49,,
Bank Sta=6.24,16.84
XS Rating Curve= 0 ,0
Exp/Cntr=0.3,0.1

Type RM Length L Ch R = 1 ,15      ,35.27,34.4,33.963
BEGIN DESCRIPTION:
S4200
S4200
END DESCRIPTION:
#Sta/Elev= 12
       01035.838     2.81030.768     5.61030.989     9.61031.747    13.11033.277
    17.61035.137    25.11035.587    29.61035.508   32.451035.048   32.451035.508
    32.61035.048    39.41035.048
#Mann= 3 , 0 , 0
       0     .06       0       0    .045       0    13.1     .06       0
Levee=-1,0.06,1035.86,-1,25.11,1035.61,,
Bank Sta=0,13.1
XS Rating Curve= 0 ,0
Exp/Cntr=0.3,0.1

Type RM Length L Ch R = 3 ,14.8    ,,,
BEGIN DESCRIPTION:
Puente Bomberos
END DESCRIPTION:
Bridge Culvert--1,0,-1,-1, 0
Deck Dist Width WeirC Skew NumUp NumDn MinLoCord MaxHiCord MaxSubmerge Is_Ogee
5,6,1.4,0, 6, 6, , , 0.98, 0, 0,0,,
       0       1       1    11.8    11.8    39.4
 1033.85 1033.85 1033.85 1033.85 1033.85 1033.85
    1030    1030 1032.85 1032.85    1030    1030
       0       6       6    16.8    16.8   38.87
 1033.85 1033.85 1033.85 1033.85 1033.85 1033.85
    1030    1030 1032.85 1032.85    1030    1030
BR Coef=-1 , 0 , 0 ,, 0 ,,,0.8,-1,,0,
WSPro=,,,, 1 ,,,, 0 ,,,, 0 ,,,,-1 ,-1 ,-1 , 0 , 0 , 0 , 0 , 0
BC Design=,, 0 ,, 0 ,,,,,,
BC Use User HTab Curves=0
BC User HTab FreeFlow(D)= 0

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
Type RM Length L Ch R = 1 ,14      ,107.5,107.05,107.05
BEGIN DESCRIPTION:
S4300
END DESCRIPTION:
#Sta/Elev= 13
       0  1032.8    10.6  1032.8    12.2  1030.2    14.5  1029.8    16.1  1029.3
    19.6    1029    23.1  1029.1      24    1030      24  1029.1    27.5  1030.5
    32.4  1032.8    36.5  1034.2    37.8  1034.2
#Mann= 3 , 0 , 0
       0     .06       0    12.2    .045       0    27.5     .06       0
Levee=-1,10.56,1032.83,-1,36.57,1034.22,,
Bank Sta=12.2,27.5
XS Rating Curve= 0 ,0
Exp/Cntr=0.3,0.1

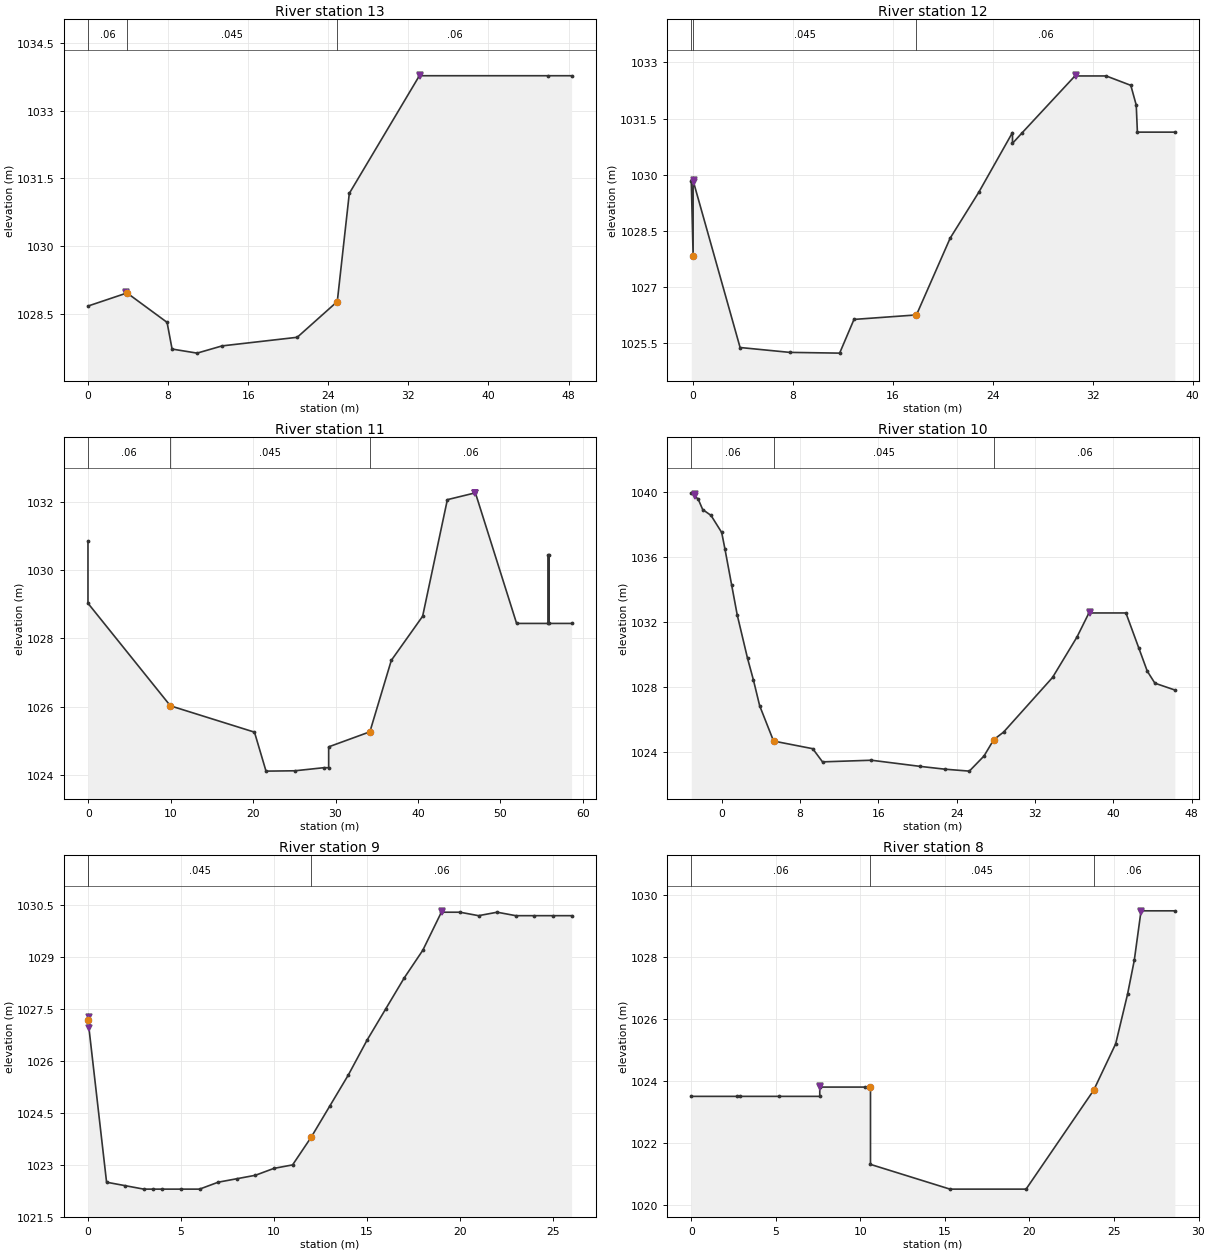
Type RM Length L Ch R = 1 ,13      ,93.38,95.3,98.8
BEGIN DESCRIPTION:
S4400
END DESCRIPTION:
#Sta/Elev= 12
       0 1028.68     3.9 1028.97     7.9 1028.32     8.4 1027.73    10.9 1027.64
    13.4  1027.8    20.9 1027.99    24.9 1028.78    26.1 1031.17    33.1 1033.77
    45.9 1033.77  48.301 1033.77
#Mann= 3 , 0 , 0
       0     .06       0     3.9    .045       0    24.9     .06       0
Levee=-1,3.82,1028.99,-1,33.17,1033.79,,
Bank Sta=3.9,24.9
XS Rating Curve= 0 ,0
Exp/Cntr=0.3,0.1

Type RM Length L Ch R = 1 ,12      ,98.76,99.1,99.63
BEGIN DESCRIPTION:
S4500
END DESCRIPTION:
#Sta/Elev= 19
    -.151029.845       0 1027.84       01029.845    3.76 1025.39    7.73 1025.26
   11.73 1025.24   12.88 1026.14   17.88 1026.26   20.58 1028.31   22.88 1029.54
   25.57 1031.13   25.57 1030.84  26.363 1031.13   30.57 1032.64   33.07 1032.64
  35.0431032.389  35.4771031.862   35.57 1031.14   38.57 1031.14
#Mann= 3 , 0 , 0
    -.15     .06       0       0    .045       0   17.88     .06       0
Levee=-1,0.04,1029.86,-1,30.62,1032.67,,
Bank Sta=0,17.88
XS Rating Curve= 0 ,0
Exp/Cntr=0.3,0.1

Type RM Length L Ch R = 1 ,11      ,107.91,104.2,96.66
BEGIN DESCRIPTION:
S4600
END DESCRIPTION:
#Sta/Elev= 20
    -.03 1030.85    -.03 1029.03    9.97 1026.03   20.17 1025.26   21.57 1024.12
   25.07 1024.13   28.57 1024.22   29.17 1024.22   29.17 1024.83   34.17 1025.27
   36.77 1027.36   40.57 1028.65   43.57 1032.06   46.97 1032.26   51.97 1028.44
   55.77 1028.44   55.77 1030.44   55.92 1030.44   55.92 1028.44   58.64 1028.44
#Mann= 3 , 0 , 0
    -.03     .06       0    9.97    .045       0   34.17     .06       0
Levee=-1,-0.11,1030.87,-1,46.97,1032.26,,
Bank Sta=9.97,34.17
XS Rating Curve= 0 ,0
Exp/Cntr=0.3,0.1

Type RM Length L Ch R = 1 ,10      ,104.3,102.8,101.55
BEGIN DESCRIPTION:
S4700
END DESCRIPTION:
#Sta/Elev= 29
   -3.11 1039.97    -2.4 1039.58   -1.94 1038.94   -1.09 1038.58       0 1037.53
     .34 1036.49    1.02 1034.29    1.59 1032.45    2.64 1029.79    3.24 1028.46
    3.88 1026.87     5.3  1024.7     9.3 1024.23    10.3 1023.42    15.3 1023.52
    20.3 1023.14    22.8 1022.97    25.3 1022.85    26.8 1023.78    27.8 1024.79
    28.8 1025.25    33.8 1028.61    36.3  1031.1   37.52 1032.58    41.3 1032.58
   42.63  1030.4   43.48    1029   44.26 1028.26    46.3 1027.84
#Mann= 3 , 0 , 0
   -3.11     .06       0     5.3    .045       0    27.8     .06       0
Levee=-1,-2.77,1039.91,-1,37.58,1032.65,,
Bank Sta=5.3,27.8
XS Rating Curve= 0 ,0
Exp/Cntr=0.3,0.1

Type RM Length L Ch R = 1 ,9       ,102.56,100.5,99.53
BEGIN DESCRIPTION:
S4800
END DESCRIPTION:
#Sta/Elev= 28
       0  1027.2       1  1022.5       2  1022.4       3  1022.3     3.5  1022.3
       4  1022.3       5  1022.3       6  1022.3       7  1022.5       8  1022.6
       9  1022.7      10  1022.9      11    1023      12  1023.8      13  1024.7
      14  1025.6      15  1026.6      16  1027.5      17  1028.4      18  1029.2
      19  1030.3      20  1030.3      21  1030.2      22  1030.3      23  1030.2
      24  1030.2      25  1030.2      26  1030.2
#Mann= 3 , 0 , 0
       0     .06       0       0    .045       0      12     .06       0
Levee=-1,0.05,1027.27,-1,19.02,1030.34,,
Bank Sta=0,12
XS Rating Curve= 0 ,0
Exp/Cntr=0.3,0.1

Type RM Length L Ch R = 1 ,8       ,93.7,95.2,97.16
BEGIN DESCRIPTION:
S4900
END DESCRIPTION:
#Sta/Elev= 17
       0  1023.5     2.7  1023.5     2.9  1023.5     5.2  1023.5     7.6  1023.5
     7.6  1023.8    10.3  1023.8    10.6  1023.8    10.6  1021.3    15.3  1020.5
    19.8  1020.5    23.8  1023.7    25.1  1025.2    25.8  1026.8    26.2  1027.9
    26.6  1029.5    28.6  1029.5
#Mann= 3 , 0 , 0
       0     .06       0    10.6    .045       0    23.8     .06       0
Levee=-1,7.64,1023.84,-1,26.59,1029.49,,
Bank Sta=10.6,23.8
XS Rating Curve= 0 ,0
Exp/Cntr=0.3,0.1

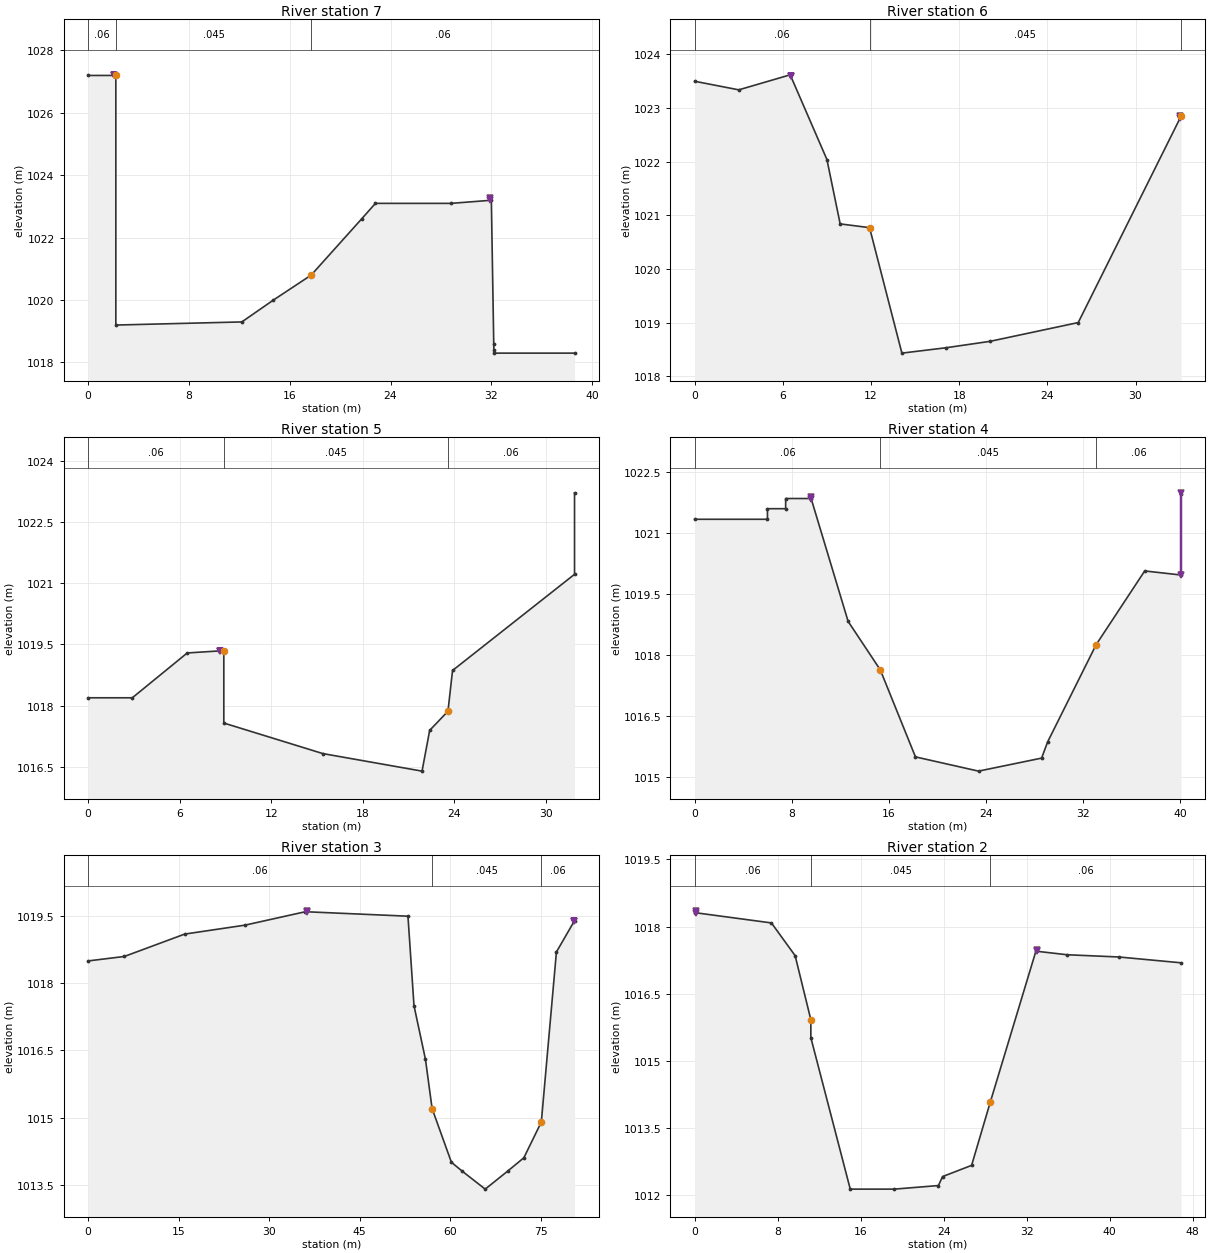
Type RM Length L Ch R = 1 ,7       ,97.23,96.7,96.15
BEGIN DESCRIPTION:
S5000
END DESCRIPTION:
#Sta/Elev= 14
       0  1027.2     2.2  1027.2     2.2  1019.2    12.2  1019.3    14.7    1020
    17.7  1020.8    21.7  1022.6    22.8  1023.1    28.8  1023.1      32  1023.2
   32.19 1018.59    32.2  1018.4    32.2  1018.3    38.6  1018.3
#Mann= 3 , 0 , 0
       0     .06       0     2.2    .045       0    17.7     .06       0
Levee=-1,2.07,1027.22,-1,31.91,1023.27,,
Bank Sta=2.2,17.7
XS Rating Curve= 0 ,0
Exp/Cntr=0.3,0.1

Type RM Length L Ch R = 1 ,6       ,98.6,99.8,100.67
BEGIN DESCRIPTION:
S5100
END DESCRIPTION:
#Sta/Elev= 11
       0  1023.5       3 1023.34     6.5 1023.62       9 1022.04     9.9 1020.84
    11.9 1020.77    14.1 1018.43    17.1 1018.53    20.1 1018.65    26.1    1019
    33.1 1022.85
#Mann= 3 , 0 , 0
       0     .06       0    11.9    .045       0    33.1     .06       0
Levee=-1,6.54,1023.6,-1,33.03,1022.86,,
Bank Sta=11.9,33.1
XS Rating Curve= 0 ,0
Exp/Cntr=0.3,0.1

Type RM Length L Ch R = 1 ,5       ,114.36,110.1,106.32
BEGIN DESCRIPTION:
S5200
END DESCRIPTION:
#Sta/Elev= 13
       0 1018.19     2.9 1018.19     6.5 1019.29     8.6 1019.34     8.9 1019.34
     8.9 1017.57    15.4 1016.82    21.9 1016.39    22.4 1017.39    23.6 1017.86
    23.9 1018.86    31.9 1021.22    31.9 1023.22
#Mann= 3 , 0 , 0
       0     .06       0     8.9    .045       0    23.6     .06       0
Levee=-1,8.62,1019.34,-1,31.92,1023.23,,
Bank Sta=8.9,23.6
XS Rating Curve= 0 ,0
Exp/Cntr=0.3,0.1

Type RM Length L Ch R = 1 ,4       ,99.67,99.78,99.96
BEGIN DESCRIPTION:
S5300
END DESCRIPTION:
#Sta/Elev= 16
       0 1021.34       6 1021.34       6  1021.6     7.5  1021.6     7.5 1021.85
     9.6 1021.85   12.65 1018.83    15.3 1017.64    18.2  1015.5    23.4 1015.15
    28.6 1015.47    29.1 1015.87    33.1 1018.26    37.1 1020.07    40.1 1019.97
    40.1 1021.97
#Mann= 3 , 0 , 0
       0     .06       0    15.3    .045       0    33.1     .06       0
Levee=-1,9.61,1021.88,-1,40.08,1021.99,,
Bank Sta=15.3,33.1
XS Rating Curve= 0 ,0
Exp/Cntr=0.3,0.1

Type RM Length L Ch R = 1 ,3       ,98.3,100.2,101.13
BEGIN DESCRIPTION:
S5400
END DESCRIPTION:
#Sta/Elev= 17
       0  1018.5       6  1018.6      16  1019.1      26  1019.3      36  1019.6
      53  1019.5      54  1017.5    55.9  1016.3      57  1015.2    60.2    1014
      62  1013.8    65.8  1013.4    69.5  1013.8    72.2  1014.1    75.1  1014.9
    77.6  1018.7    80.6  1019.4
#Mann= 3 , 0 , 0
       0     .06       0      57    .045       0    75.1     .06       0
Levee=-1,36.22,1019.62,-1,80.54,1019.39,,
Bank Sta=57,75.1
XS Rating Curve= 0 ,0
Exp/Cntr=0.3,0.1

Type RM Length L Ch R = 1 ,2       ,96.77,97.2,98.44
BEGIN DESCRIPTION:
S5500
END DESCRIPTION:
#Sta/Elev= 15
       0 1018.31     7.4 1018.08   9.685 1017.35    11.2 1015.92    11.2 1015.52
      15 1012.14   19.25 1012.14    23.5 1012.22    23.9 1012.42    26.7 1012.67
    28.5 1014.08    32.9 1017.45    35.9 1017.37    40.9 1017.32    46.9 1017.19
#Mann= 3 , 0 , 0
       0     .06       0    11.2    .045       0    28.5     .06       0
Levee=-1,0.12,1018.35,-1,33.01,1017.48,,
Bank Sta=11.2,28.5
XS Rating Curve= 0 ,0
Exp/Cntr=0.3,0.1

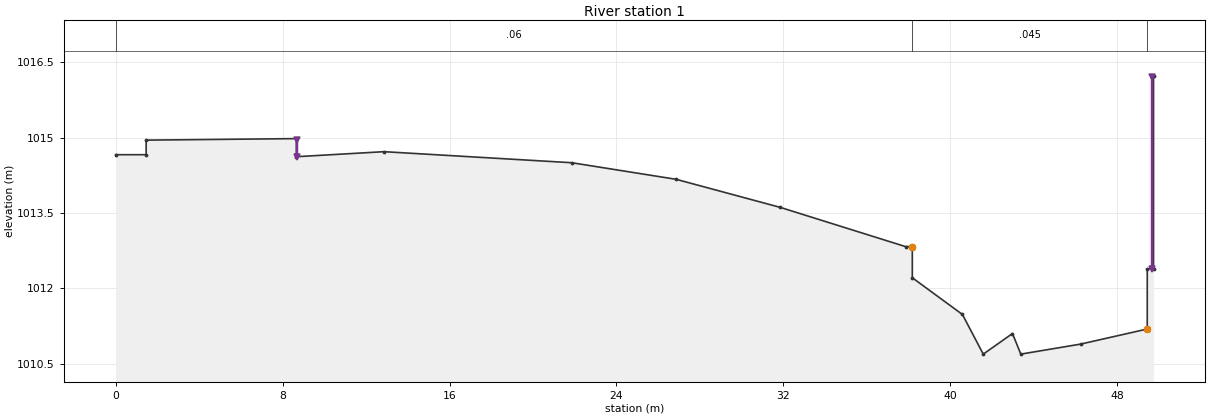
Type RM Length L Ch R = 1 ,1       ,0,0,0
BEGIN DESCRIPTION:
S5600
END DESCRIPTION:
#Sta/Elev= 21
       0 1014.66    1.46 1014.66    1.46 1014.95    8.66 1014.98    8.66 1014.62
   12.86 1014.72   21.86  1014.5   26.86 1014.17   31.86 1013.61   37.86 1012.83
   38.18 1012.83   38.18 1012.21   40.58 1011.48   41.58 1010.69   42.98  1011.1
   43.38 1010.69   46.25 1010.89   49.44 1011.19   49.44 1012.39   49.74 1012.39
   49.74 1016.23
#Mann= 3 , 0 , 0
       0     .06       0   38.18    .045       0   49.44     .06       0
Levee=-1,8.69,1014.95,-1,49.69,1016.21,,
Bank Sta=38.18,49.44
XS Rating Curve= 0 ,0
Exp/Cntr=0.3,0.1

Chan Stop Cuts=-1
Use User Specified Reach Order=0